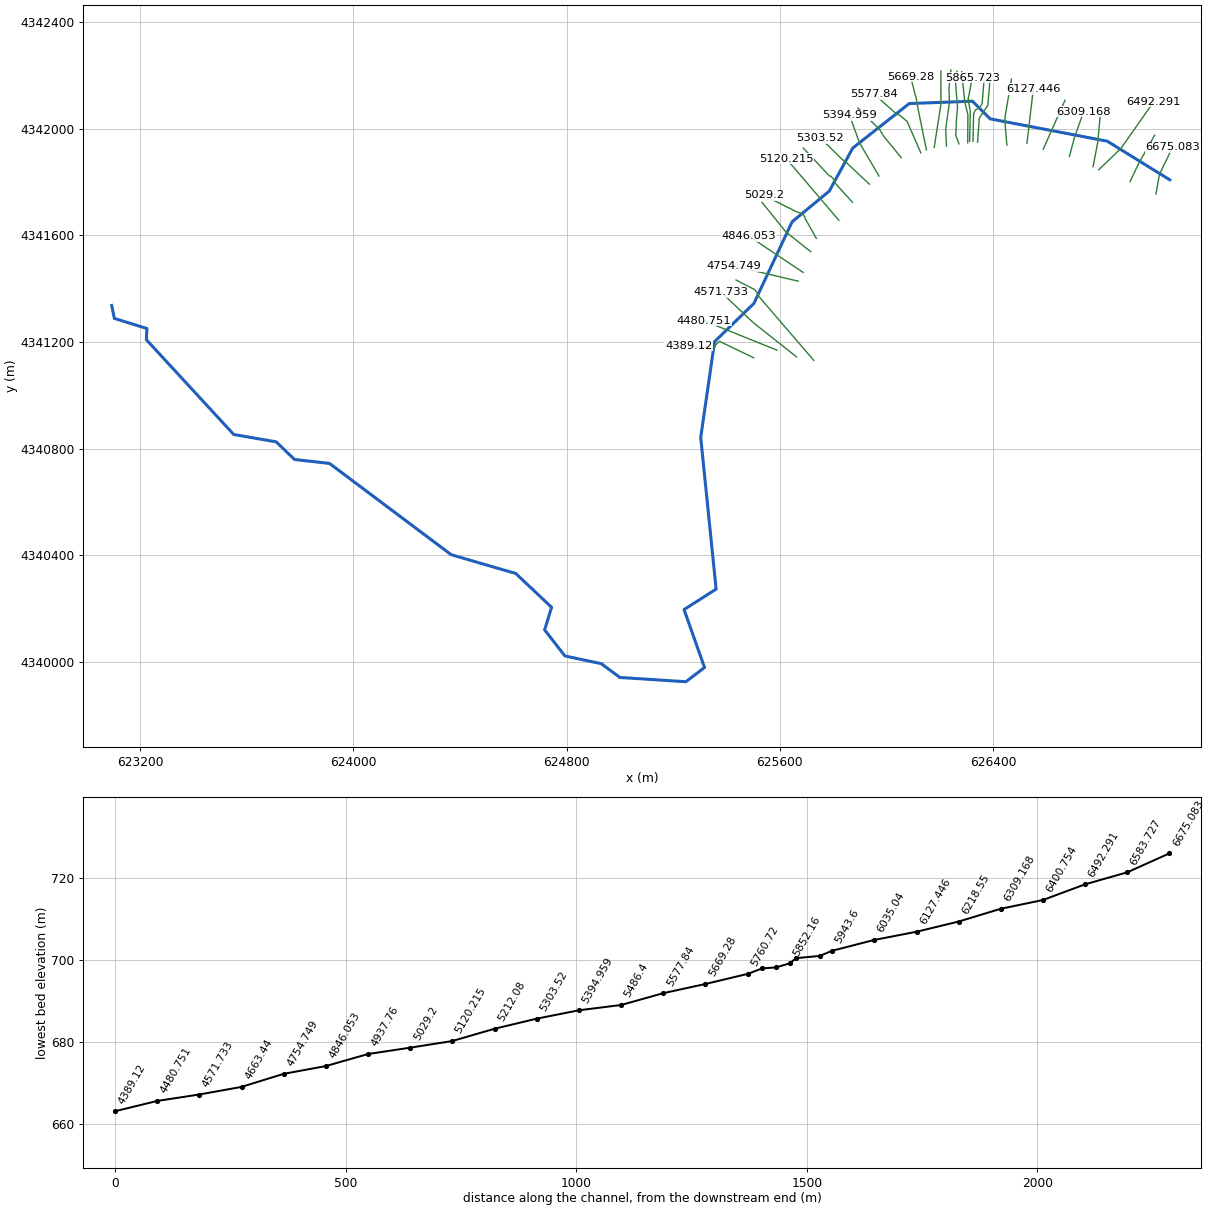
--- LeadmineRun.prj (project) ---

Proj Title=LeadmineRun
Current Plan=p01
Default Exp/Contr=0.3,0.1
SI Units
Geom File=g01
Flow File=f01
Plan File=p01
Y Axis Title=Elevation
X Axis Title(PF)=Main Channel Distance
X Axis Title(XS)=Station
BEGIN DESCRIPTION:
September 2018
Tucker County ABFE Study
US Army Corps of Engineers, Pittsburgh District
NAD 1983 UTM 17N (meters)
END DESCRIPTION:
DSS Export Rating Curves= 0
DSS Export Rating Curve Sorted= 0
DSS Export Volume Flow Curves= 0
DXF OffsetX= 0
DXF OffsetY= 0
DXF ScaleX= 1
DXF ScaleY= 10

--- LeadmineRun.p01 (plan) ---

Plan Title=LeadmineRun_plan
Program Version=5.05
Short Identifier=Plan1_subcritical
Geom File=g01
Flow File=f01
Subcritical Flow
K Sum by GR= 0
Std Step Tol= 0.003
Critical Tol= 0.003
Num of Std Step Trials= 20
Max Error Tol= 0.1
Flow Tol Ratio= 0.001
Split Flow NTrial= 30
Split Flow Tol= 0.006
Split Flow Ratio= 0.02
Log Output Level= 0
Friction Slope Method= 1
Unsteady Friction Slope Method= 2
Unsteady Bridges Friction Slope Method= 1
Parabolic Critical Depth
Global Vel Dist= 0 , 0 , 0
Global Log Level= 0
CheckData=True
Encroach Param=-1 ,0,0, 0
Computation Interval=1MIN
Output Interval=1HOUR
Instantaneous Interval=1HOUR
Mapping Interval=1HOUR
Computation Time Step Use Courant=        0
Computation Time Step Use Time Series=    0
Computation Time Step Count To Double=0
Computation Time Step Max Doubling=0
Computation Time Step Max Halving=0
Computation Time Step Residence Courant=0
Run HTab= 0
Run UNet= 0
Run Sediment= 0
Run PostProcess= 0
Run WQNet= 0
Run RASMapper=-1
UNET Theta= 1
UNET Theta Warmup= 1
UNET ZTol= 0.006
UNET ZSATol= 0.006
UNET MxIter= 20
UNET Max Iter WO Improvement= 0
UNET MaxInSteps= 0
UNET DtIC= 0
UNET DtMin= 0
UNET MaxCRTS= 20
UNET WFStab= 2
UNET SFStab= 1
UNET WFX= 1
UNET SFX= 1
UNET 1D Methodology=Finite Difference
UNET DSS MLevel= 4
UNET Pardiso=0
UNET DZMax Abort= 30
UNET Use Existing IB Tables=-1
UNET Froude Reduction=False
UNET Froude Limit= 0.8
UNET Froude Power= 4
UNET D1 Cores= 0
UNET D2 Coriolis=0
UNET D2 Cores= 0
UNET D2 Theta= 1
UNET D2 Theta Warmup= 1
UNET D2 Z Tol= 0.003
UNET D2 Volume Tol= 0.003
UNET D2 Max Iterations= 20
UNET D2 Equation= 0
UNET D2 RampUpFraction=0.1
UNET D2 TimeSlices= 1
UNET D2 BCVolumeCheck=0
UNET D1D2 MaxIter= 0
UNET D1D2 ZTol=0.003
UNET D1D2 QTol=0.1
UNET D1D2 MinQTol=0.03
Write IC File= 0
Write IC File at Fixed DateTime=0
Write IC File at Sim End=0
Echo Input=False
Echo Parameters=False
Echo Output=False
Write Detailed= 0
HDF Write Warmup=0
HDF Write Time Slices=0
HDF Flush=0
HDF Face Node Velocities=0
HDF Compression= 1
HDF Chunk Size= 1
HDF Spatial Parts= 1
HDF Use Max Rows=0
HDF Fixed Rows= 1
Calibration Method= 0
Calibration Iterations= 20
Calibration Max Change=0.05
Calibration Tolerance=0.2
Calibration Maximum=1.5
Calibration Minimum=0.5
Calibration Optimization Method= 1
WQ AD Non Conservative
WQ ULTIMATE=-1
WQ Max Comp Step=1HOUR
WQ Output Interval=15MIN
WQ Output Selected Increments= 0
WQ Output face flow=0
WQ Output face velocity=0
WQ Output face area=0
WQ Output face dispersion=0
WQ Output cell volume=0
WQ Output cell surface area=0
WQ Output cell continuity=0
WQ Output cumulative cell continuity=0
WQ Output face conc=0
WQ Output face dconc_dx=0
WQ Output face courant=0
WQ Output face peclet=0
WQ Output face adv mass=0
WQ Output face disp mass=0
WQ Output cell mass=0
WQ Output cell source sink temp=0
WQ Output nsm pathways=0
WQ Output nsm derived pathways=0
WQ Output MaxMinRange=-1
WQ Daily Max Min Mean=-1
WQ Daily Range=0
WQ Daily Time=0
WQ Create Restart=0
WQ Fixed Restart=0
WQ System Summary=0
WQ Write To DSS=0
WQ Use Fixed Temperature=0
Sorting and Armoring Iterations= 10
XS Update Threshold= 0.02
Bed Roughness Predictor= 0
Hydraulics Update Threshold= 0.02
Energy Slope Method= 1
Volume Change Method= 1
Sediment Retention Method= 0
XS Weighting Method= 0
Number of US Weighted Cross Sections= 1
Number of DS Weighted Cross Sections= 1
Upstream XS Weight=0
Main XS Weight=1
Downstream XS Weight=0
Number of DS XS's Weighted with US Boundary= 1
Upstream Boundary Weight= 1
Weight of XSs Associated with US Boundary= 0
Number of US XS's Weighted with DS Boundary= 1
Downstream Boundary Weight= 0.5
Weight of XSs Associated with DS Boundary= 0.5
Percentile Method= 0
Sediment Output Level= 4
Mass or Volume Output= 0
Output Increment Type= 1
Profile and TS Output Increment= 1
XS Output Flag= 0
XS Output Increment= 10
Write Gradation File= 0
Read Gradation Hotstart= 0
Write HDF5 File= 1
Write Binary Output= 1
Write DSS Sediment File= 0
SV Curve= 0
Specific Gage Flag= 0

--- LeadmineRun.f01 (steady flow) ---

Flow Title=LeadmineRun_flow
Program Version=5.05
Number of Profiles= 1
Profile Names=PF 1
River Rch & RM=Leadmine Run,1               ,6675.083
   14.64
River Rch & RM=Leadmine Run,1               ,5760.72
 17.7262
River Rch & RM=Leadmine Run,1               ,4571.733
 20.8693
River Rch & RM=Leadmine Run,1               ,4023.36
 21.4356
River Rch & RM=Leadmine Run,1               ,3017.46
 31.3181
River Rch & RM=Leadmine Run,1               ,2926.037
 31.3748
River Rch & RM=Leadmine Run,1               ,1554.48
 34.5462
River Rch & RM=Leadmine Run,1               ,457.2
 35.8488
River Rch & RM=Leadmine Run,1               ,91.44003
  36.047
Boundary for River Rch & Prof#=Leadmine Run,1               , 1
Up Type= 2
Dn Type= 1
Dn Known WS=562.05
DSS Import GetInterval= 0
DSS Import GetPeak= 0
DSS Import FillOption= 0

--- LeadmineRun.g01 (geometry) ---

Geom Title=LeadmineRun_geometry
Program Version=5.05

River Reach=Leadmine Run    ,1
Reach XY= 30
     627062.6643    4341808.6917      626828.235     4341953.551
     626389.0464    4342037.3771     626322.7766    4342103.5726
     626085.4765    4342094.7372     625873.8094    4341928.0493
     625785.3943    4341766.3004625646.2254128054341651.30033598
625502.8702167694341345.22992561625355.2526126054341201.54678234
     625303.3666    4340842.1972     625361.1389    4340273.5061
625240.8868384144340196.92417637     625317.6541    4339979.6538
      625247.804    4339926.2078     625000.2978    4339942.2272
     624930.3034    4339993.9413     624794.0427    4340022.7809
     624717.9559    4340120.8092     624743.9336    4340205.4958
     624609.6277    4340332.2118624367.5486216454340402.64286204
     623911.1263    4340744.9626     623779.8927    4340759.7793
     623711.1009    4340825.9253      623551.941    4340853.4549
623224.2166256094341209.01565518623226.1264399414341251.07236509
     623104.0573    4341288.9471      623094.282    4341337.5076

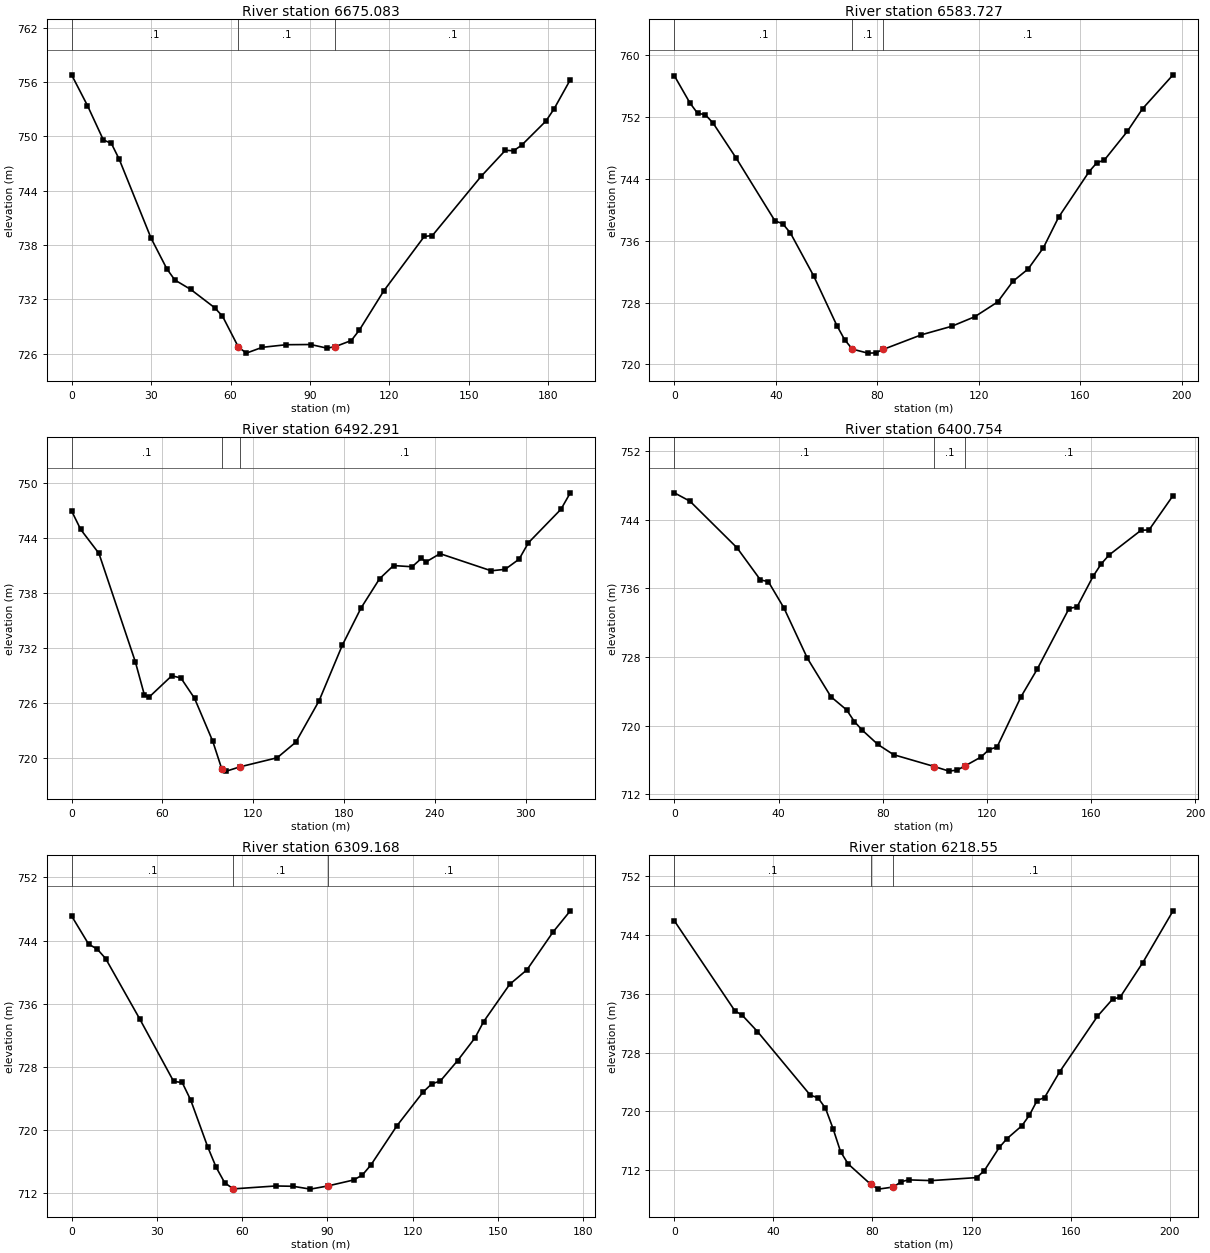
Type RM Length L Ch R = 1 ,6675.083,92.37,91.36,87.89
XS GIS Cut Line= 3
     627010.9928    4341755.4983     627023.7628    4341829.3562
     627073.4346     4341931.182
#Sta/Elev= 30
       0   756.8       6   753.4   11.99  749.61   14.99  749.24   17.99  747.47
   29.98  738.78   35.98  735.37   38.98  734.15   44.97  733.11   53.97   731.1
   56.96  730.16   62.96  726.75   65.96  726.08   71.96  726.72   81.08  727.01
   90.26  727.03   96.39  726.63   99.45  726.79  105.57  727.47  108.64  728.63
  117.82  732.94  133.13  738.96  136.19  739.06  154.57  745.59  163.75  748.47
  166.81  748.41  169.88  749.03  179.06   751.7  182.12  753.04  188.25  756.26
#Mann= 3 , 0 , 0
       0      .1       0   62.96      .1       0   99.45      .1       0
Bank Sta=62.96,99.45
XS Rating Curve= 0 ,0
Exp/Cntr=0.3,0.1

Type RM Length L Ch R = 1 ,6583.727,92.73,91.44,85.95
XS GIS Cut Line= 3
      626913.626     4341802.065     626947.7868    4341873.6562
     627005.7011     4341975.632
#Sta/Elev= 30
       0  757.36     6.1  753.86    9.15   752.5    12.2  752.32   15.25  751.24
   24.41  746.68   39.66  738.57   42.71  738.21   45.76     737   54.92  731.45
   64.07  725.02   67.12  723.19   70.17  721.97   76.27  721.45   79.32  721.48
   82.33  721.93   97.37  723.82  109.39  724.93  118.42  726.16  127.44  728.07
  133.45  730.74  139.46  732.34  145.48  735.09  151.49  739.05  163.52  744.95
  166.53  746.09  169.53  746.45  178.56  750.15  184.57  753.09   196.6  757.48
#Mann= 3 , 0 , 0
       0      .1       0   70.17      .1       0   82.33      .1       0
Bank Sta=70.17,82.33
XS Rating Curve= 0 ,0
Exp/Cntr=0.3,0.1

Type RM Length L Ch R = 1 ,6492.291,89.76,91.54,99.49
XS GIS Cut Line= 3
     626796.1507    4341846.5151     626878.7224    4341925.5823
     627002.5261     4342101.574
#Sta/Elev= 30
       0  746.92    6.02   744.9   18.05  742.29   42.12  730.45   48.14  726.81
   51.14  726.59   66.19  728.93    72.2  728.69   81.23  726.47   93.26  721.78
   99.28  718.73  102.29  718.52  111.31  718.99  135.84  719.98  148.14  721.68
  163.51   726.2  178.88  732.27  191.17  736.31  203.47  739.52  212.69  740.96
  224.98  740.83  231.13  741.74  234.21  741.36  243.43  742.26  277.24  740.39
  286.46  740.55  295.68  741.66  301.83  743.45  323.35  747.11   329.5   748.9
#Mann= 3 , 0 , 0
       0      .1       0   99.28      .1       0  111.31      .1       0
Bank Sta=99.28,111.31
XS Rating Curve= 0 ,0
Exp/Cntr=0.3,0.1

Type RM Length L Ch R = 1 ,6400.754,90.61,91.59,88.65
XS GIS Cut Line= 3
      626774.984    4341858.1568     626792.5007    4341949.7002
     626801.4424    4342047.5989
#Sta/Elev= 30
       0  747.16    6.01  746.18   24.05  740.75   33.07  736.99   36.08   736.8
   42.09  733.72   51.11  727.84   60.13  723.36   66.14  721.83   69.15  720.46
   72.16  719.46   78.17  717.79   84.18   716.6   99.79  715.22  105.49  714.68
  108.56   714.8  111.64  715.29  117.78  716.33  120.85   717.2  123.92  717.49
  133.14  723.37  139.29  726.55  151.57  733.66  154.65  733.85  160.79  737.41
  163.86  738.84  166.93   739.9  179.22  742.79  182.29  742.83  191.51  746.84
#Mann= 3 , 0 , 0
       0      .1       0   99.79      .1       0  111.64      .1       0
Bank Sta=99.79,111.64
XS Rating Curve= 0 ,0
Exp/Cntr=0.3,0.1

Type RM Length L Ch R = 1 ,6309.168,91.79,90.62,89.35
XS GIS Cut Line= 3
     626686.0838    4341896.2569     626704.6459    4341965.6618
     626739.0006    4342063.4739
#Sta/Elev= 30
       0  747.11    5.99  743.54    8.98  742.93   11.97  741.72   23.95  734.09
   35.92  726.16   38.92  726.03   41.91  723.81    47.9  717.88   50.89  715.28
   53.88  713.34   56.88  712.56   71.84  712.93   77.94  712.89   84.04  712.53
   90.14  712.93   99.29  713.69  102.34  714.32  105.38  715.61  114.53  720.57
  123.68  724.81  126.73  725.85  129.78  726.22  135.88  728.81  141.97  731.68
  145.02  733.74  154.17  738.45  160.27   740.3  169.42  745.07  175.51  747.76
#Mann= 3 , 0 , 0
       0      .1       0   56.88      .1       0   90.14      .1       0
Bank Sta=56.88,90.14
XS Rating Curve= 0 ,0
Exp/Cntr=0.3,0.1

Type RM Length L Ch R = 1 ,6218.55 ,90.02,91.1,96.15
XS GIS Cut Line= 2
      626587.835    4341923.3106      626669.856    4342107.1964
#Sta/Elev= 30
       0  745.95   24.41  733.71   27.46  733.08   33.56  730.88   54.91  722.21
   57.96  721.87   61.01  720.45   64.07  717.67   67.12  714.52   70.17  712.86
   79.32  710.07   82.37  709.43   88.47  709.72   91.52  710.43   94.57  710.69
  103.73  710.59  122.03     711  125.08  711.91  131.18   715.1  134.23  716.28
  140.33  718.06  143.38  719.51  146.44  721.48  149.49   721.9  155.59  725.41
  170.84  732.96  176.94  735.29  179.99  735.56  189.15  740.27  201.35  747.31
#Mann= 3 , 0 , 0
       0      .1       0   79.32      .1       0   88.47      .1       0
Bank Sta=79.32,88.47
XS Rating Curve= 0 ,0
Exp/Cntr=0.3,0.1

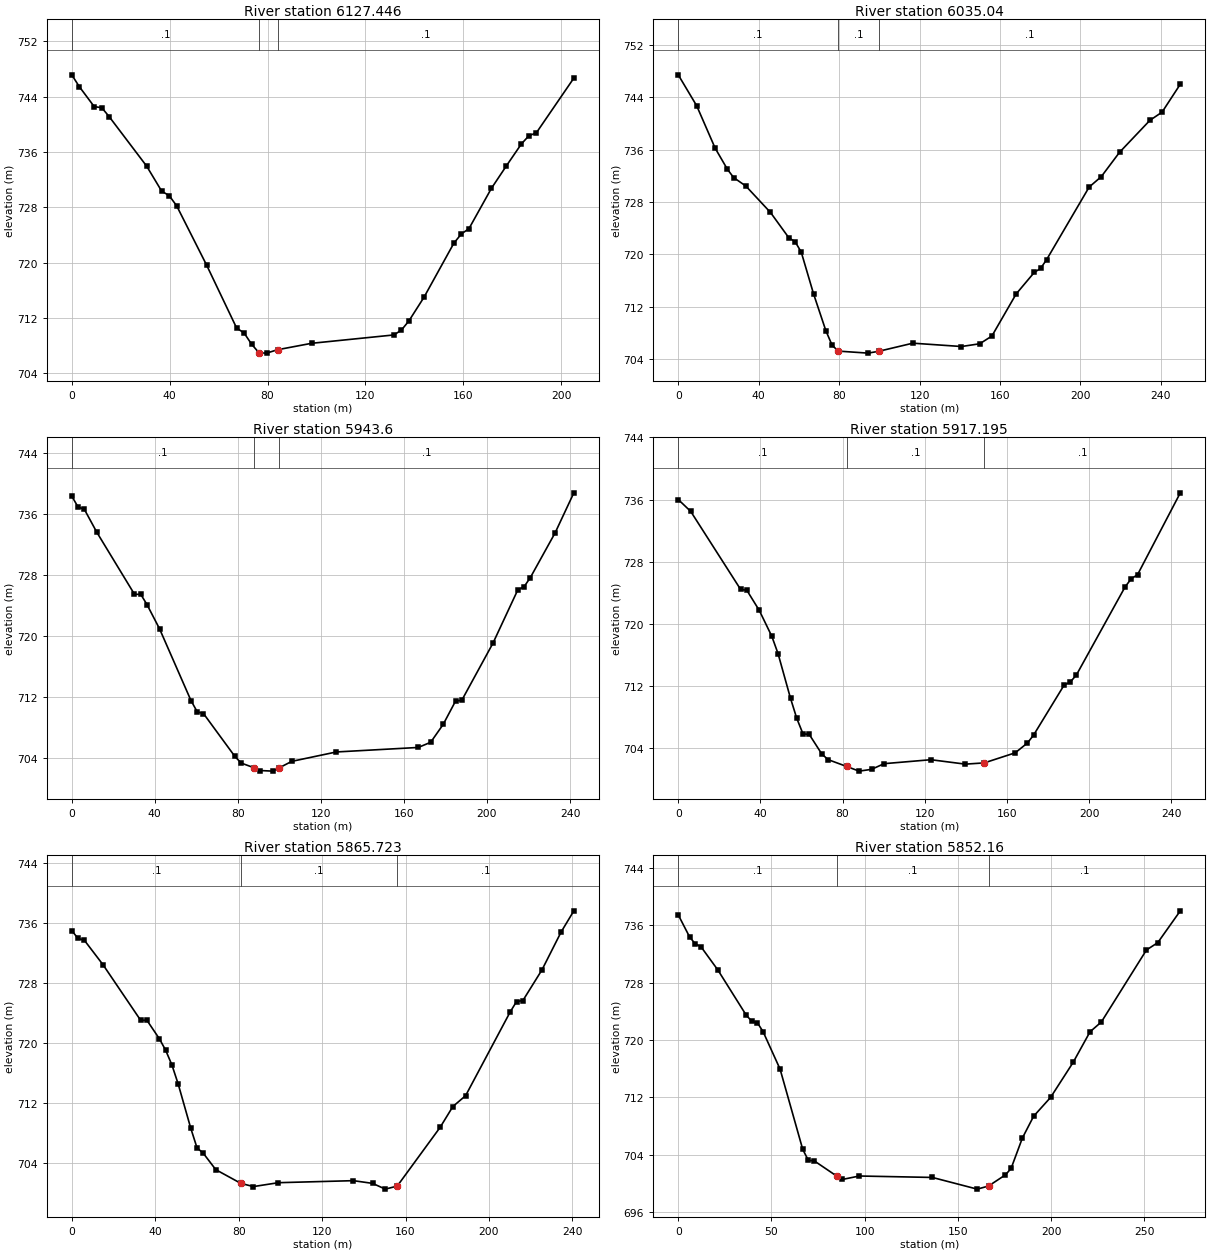
Type RM Length L Ch R = 1 ,6127.446,91.96,92.41,92.55
XS GIS Cut Line= 2
     626526.9807    4341945.8002     626550.7933    4342149.5298
#Sta/Elev= 30
       0  747.17    3.06  745.47    9.18  742.57   12.25  742.42   15.31  741.11
   30.61  733.96   36.74  730.35    39.8  729.71   42.86  728.23   55.11  719.65
   67.35  710.57   70.41  709.85   73.47  708.23   76.54  706.97    79.6  706.94
   84.05  707.43   97.97  708.36  131.64  709.57   134.7  710.28  137.76  711.61
  143.89  715.01  156.13  722.85  159.19  724.18  162.26  724.93  171.44  730.76
  177.56  734.01  183.69  737.18  186.75  738.36  189.81  738.79  205.12   746.7
#Mann= 3 , 0 , 0
       0      .1       0   76.54      .1       0   84.05      .1       0
Bank Sta=76.54,84.05
XS Rating Curve= 0 ,0
Exp/Cntr=0.3,0.1

Type RM Length L Ch R = 1 ,6035.04 ,94.98,91.44,79.41
XS GIS Cut Line= 4
     626451.5743    4341939.1856      626444.182    4342030.6541
     626445.1264    4342046.4727     626468.7723    4342186.5715
#Sta/Elev= 30
       0  747.44    9.18  742.71   18.35  736.24   24.47     733   27.53  731.75
   33.65  730.44   45.88  726.41   55.06  722.52   58.12  721.95   61.18  720.35
    67.3  713.97   73.41  708.35   76.47  706.16   79.53  705.23   94.41  704.92
   99.69   705.2  116.68  706.44  140.87  705.93  149.94  706.35  155.98  707.53
  168.07  713.97  177.14  717.28  180.17  717.85  183.19   719.2  204.35  730.29
   210.4  731.89  219.46   735.6  234.58  740.49  240.62  741.74  249.69  746.01
#Mann= 3 , 0 , 0
       0      .1       0   79.53      .1       0   99.69      .1       0
Bank Sta=79.53,99.69
XS Rating Curve= 0 ,0
Exp/Cntr=0.3,0.1

Type RM Length L Ch R = 1 ,5943.6  ,27.83,26.41,20.87
XS GIS Cut Line= 4
      626341.772     4341949.769     626348.1311    4342040.1884
      626380.477    4342088.6501     626388.0742    4342181.2799
#Sta/Elev= 30
       0  738.29    3.02  736.86    6.04  736.57   12.09  733.54   30.21  725.43
   33.24  725.42   36.26  724.07    42.3   720.9   57.41  711.52   60.43  710.04
   63.45  709.81   78.56   704.2   81.58  703.33   87.62  702.73   90.64  702.35
   96.78  702.27   99.84  702.69  105.98  703.55  127.44  704.78   166.9  705.37
  172.89  706.05  178.89  708.38  184.88  711.45  187.88  711.55  202.87  719.02
  214.87  726.02  217.86  726.42  220.86   727.6  232.85  733.49  241.85  738.72
#Mann= 3 , 0 , 0
       0      .1       0   87.62      .1       0   99.84      .1       0
Bank Sta=87.62,99.84
XS Rating Curve= 0 ,0
Exp/Cntr=0.3,0.1

Type RM Length L Ch R = 1 ,5917.195,19.6,51.47,54.92
XS GIS Cut Line= 6
     626324.6517    4341952.8432     626326.7684    4342056.0309
     626333.9783    4342071.4429     626348.8611    4342078.3882
      626358.783    4342093.9325     626366.0591    4342182.8989
#Sta/Elev= 30
       0     736    6.07  734.47   30.36  724.42   33.39  724.31   39.46  721.71
   45.53  718.39   48.57  716.16   54.64   710.4   57.68  707.82   60.71  705.82
   63.75  705.75   69.82  703.25   72.85  702.51   81.96  701.62   88.03  701.02
    94.1  701.25  100.17  701.98  122.96  702.49  139.72  701.92  148.94  702.08
  164.02  703.38  169.97  704.65  172.94  705.66  187.82  712.11  190.79  712.49
  193.77   713.4  217.57  724.79  220.55  725.81  223.52  726.31  244.35  736.86
#Mann= 3 , 0 , 0
       0      .1       0   81.96      .1       0  148.94      .1       0
Bank Sta=81.96,148.94
XS Rating Curve= 0 ,0
Exp/Cntr=0.3,0.1

Type RM Length L Ch R = 1 ,5865.723,12.05,13.56,14.01
XS GIS Cut Line= 6
     626311.8326    4341952.9358     626314.4996    4342063.9834
     626310.5838    4342087.5843     626306.7738     4342105.576
     626306.8796    4342113.5135     626321.6302    4342191.5049
#Sta/Elev= 30
       0     735       3  733.95       6  733.72   15.01  730.43   33.02  723.02
   36.03  723.02   42.03  720.54   45.03  719.01   48.03  717.04   51.04  714.49
   57.04  708.61   60.04  705.99   63.05  705.26   69.05  703.07   81.06  701.24
   87.06  700.81   99.07  701.33     135   701.6   144.2  701.24  150.33  700.47
  156.04  700.88   176.6  708.72   182.7   711.5  188.81  712.95  210.18  724.13
  213.23  725.52  216.28  725.66  225.44  729.76   234.6  734.81  240.71  737.64
#Mann= 3 , 0 , 0
       0      .1       0   81.06      .1       0  156.04      .1       0
Bank Sta=81.06,156.04
XS Rating Curve= 0 ,0
Exp/Cntr=0.3,0.1

Type RM Length L Ch R = 1 ,5852.16 ,36.14,29.8,28.98
XS GIS Cut Line= 4
     626304.7303    4341947.1231     626305.3458    4342053.3359
     626293.2721    4342102.9726     626282.2407    4342214.3528
#Sta/Elev= 30
       0  737.47    6.07   734.4     9.1  733.42   12.14  733.04   21.24  729.78
   36.42  723.49   39.45  722.62   42.49   722.4   45.52  721.16   54.62  715.94
   66.76  704.75    69.8  703.21   72.83  703.17   84.97  701.03   88.01  700.56
   97.11  701.04  136.26  700.84  160.32  699.21  166.37  699.64  175.45   701.2
  178.47  702.09  184.52  706.33  190.57  709.38  199.65     712  211.75  716.89
  220.82  721.16  226.87  722.52  251.07  732.57  257.12  733.59  269.22  738.03
#Mann= 3 , 0 , 0
       0      .1       0   84.97      .1       0  166.37      .1       0
Bank Sta=84.97,166.37
XS Rating Curve= 0 ,0
Exp/Cntr=0.3,0.1

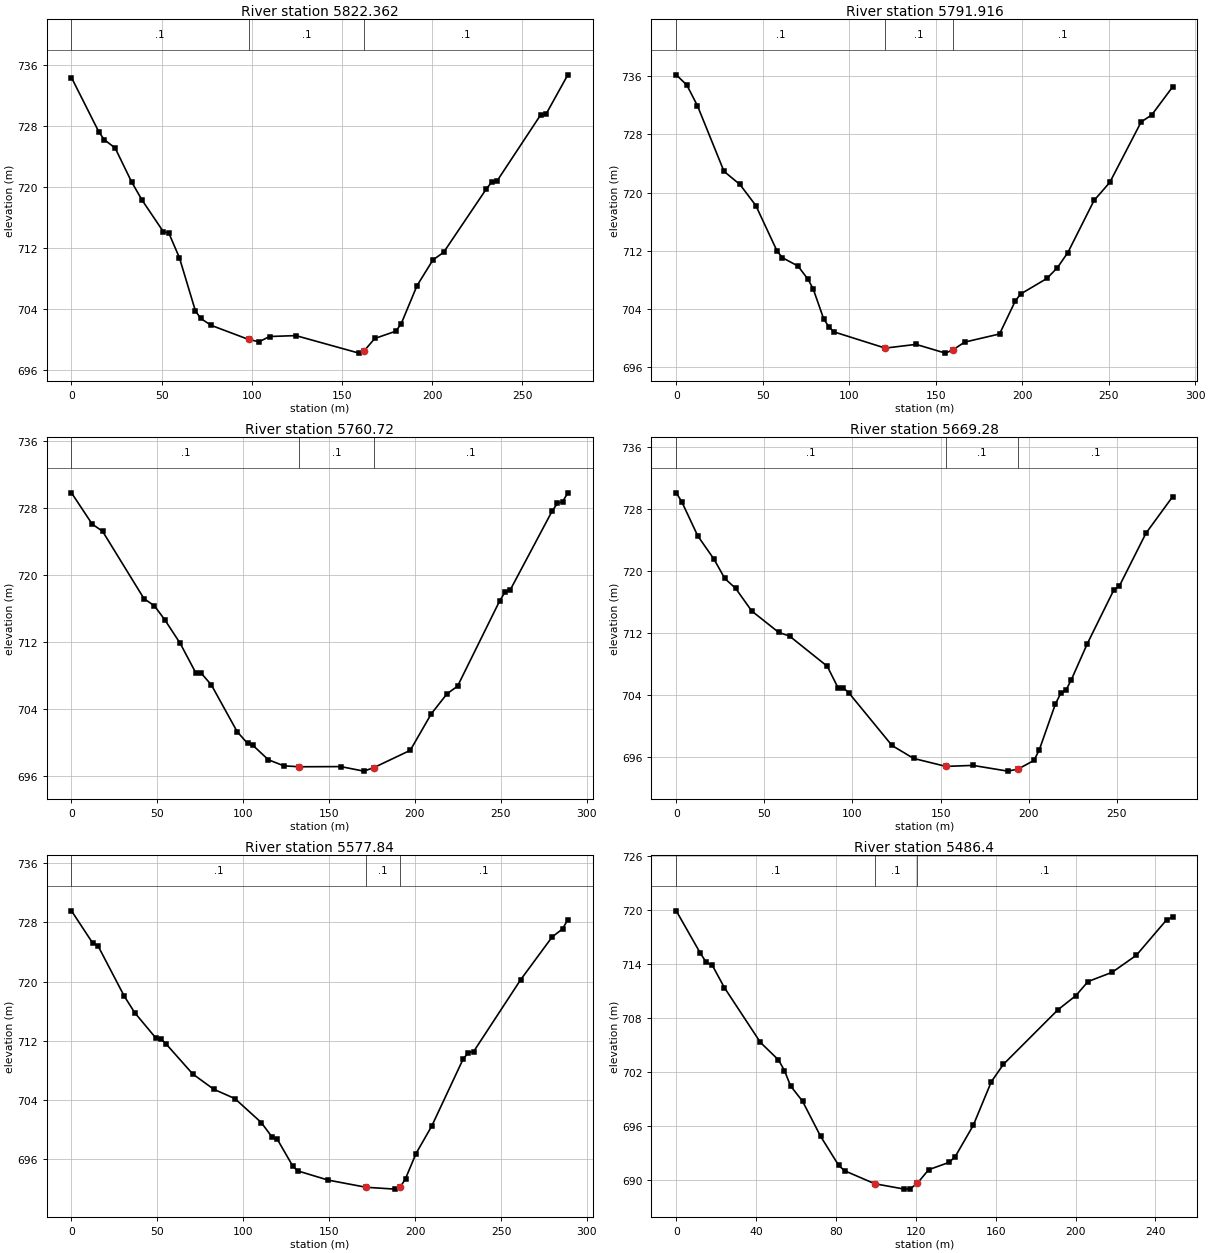
Type RM Length L Ch R = 1 ,5822.362,33.42,30.45,28.17
XS GIS Cut Line= 6
     626271.8443    4341943.7883      626259.938    4341974.8769
     626262.9146    4342039.6999     626266.7114    4342080.3532
     626259.5147    4342167.9834     626264.3831    4342216.0318
#Sta/Elev= 30
       0  734.37   15.13  727.26   18.16  726.22   24.21  725.13   33.29   720.7
   39.19  718.27   50.99  714.13   53.94  713.99   59.84  710.74   68.69  703.78
   71.64  702.76   77.53  701.85   98.18  700.01  104.01   699.7  109.85  700.39
  124.43  700.51  159.43  698.21  162.34  698.52  168.18  700.13  179.87  701.09
  182.81  702.05  191.64  707.07  200.47  710.45  206.36  711.43  229.99  719.73
     233  720.65  236.02  720.81  260.17  729.47  263.19  729.58  275.26  734.73
#Mann= 3 , 0 , 0
       0      .1       0   98.18      .1       0  162.34      .1       0
Bank Sta=98.18,162.34
XS Rating Curve= 0 ,0
Exp/Cntr=0.3,0.1

Type RM Length L Ch R = 1 ,5791.916,30.99,31.2,31.56
XS GIS Cut Line= 6
     626225.2246    4341935.1496     626222.2613    4341999.4964
     626233.4797    4342078.8716     626236.0197    4342100.8849
     626234.3263    4342151.4734     626241.9463    4342220.6885
#Sta/Elev= 30
       0  736.16    6.13  734.75   12.27  731.91   27.61  722.91   36.81  721.11
   46.01  718.22   58.28  711.98   61.35  711.06   70.35  709.92   76.29  708.07
   79.26  706.72    85.2  702.69   88.17  701.59   91.14  700.88  120.83  698.65
  138.64  699.16  155.66  697.96  159.99  698.41  166.74  699.47  186.94  700.59
  196.06  705.13   199.1  706.07  214.31  708.21  220.38  709.69  226.44  711.77
  241.58  718.92  250.66  721.39  268.82   729.7  274.88  730.64  286.99   734.5
#Mann= 3 , 0 , 0
       0      .1       0  120.83      .1       0  159.99      .1       0
Bank Sta=120.83,159.99
XS Rating Curve= 0 ,0
Exp/Cntr=0.3,0.1

Type RM Length L Ch R = 1 ,5760.72 ,85.45,91.44,94.45
XS GIS Cut Line= 4
      626179.053    4341929.9252     626203.1774    4342084.8693
     626204.3841    4342100.8132     626204.1884    4342216.9987
#Sta/Elev= 30
       0  729.78   12.06  726.05   18.09   725.2   42.22  717.17   48.25  716.32
   54.28  714.67   63.33  711.83   72.37  708.33   75.39  708.32   81.42   706.9
    96.5  701.31  102.53  699.92  105.55  699.71  114.59  697.98  123.64  697.25
  132.69  697.14  156.81  697.16  170.14  696.62  175.86  697.02  197.26   699.1
  209.49  703.45  218.66  705.84  224.78  706.74  249.24  716.88   252.3  717.91
  255.35  718.17  279.81  727.59  282.87  728.52  285.93  728.74  288.99  729.76
#Mann= 3 , 0 , 0
       0      .1       0  132.69      .1       0  175.86      .1       0
Bank Sta=132.69,175.86
XS Rating Curve= 0 ,0
Exp/Cntr=0.3,0.1

Type RM Length L Ch R = 1 ,5669.28 ,73.78,91.44,97.48
XS GIS Cut Line= 4
     626149.9487    4341920.6648     626116.2779    4342085.5907
     626112.9598    4342107.9125     626090.4174     4342195.832
#Sta/Elev= 30
       0  730.07    3.06  728.95   12.24   724.5   21.42  721.51   27.54  719.02
   33.67  717.75   42.85  714.82   58.15  712.06   64.27  711.59   85.69  707.69
   91.82  704.91   94.88  704.89   97.94  704.26  122.42  697.47  134.66   695.8
  153.03  694.77  168.33   694.9  188.07  694.16  193.92  694.42     203  695.54
  206.02  696.91   215.1  702.79  218.12  704.18  221.15  704.61  224.17  705.94
  233.25   710.6  248.38  717.57   251.4  718.02  266.53  724.85  281.66  729.57
#Mann= 3 , 0 , 0
       0      .1       0  153.03      .1       0  193.92      .1       0
Bank Sta=153.03,193.92
XS Rating Curve= 0 ,0
Exp/Cntr=0.3,0.1

Type RM Length L Ch R = 1 ,5577.84 ,99.47,91.44,88.81
XS GIS Cut Line= 6
      626128.782    4341910.0814     626077.2567    4342028.2006
     626050.0244    4342050.4601     626038.7827    4342055.7565
     626033.9744     4342058.962     625954.1567     4342129.686
#Sta/Elev= 30
       0  729.57   12.27  725.23   15.34  724.87   30.68  718.04   36.82  715.78
   49.09  712.36   52.16   712.2   55.23  711.51   70.57  707.49   82.84  705.42
   95.12  704.16  110.46  700.92   116.6     699  119.66  698.71  128.87     695
   131.8  694.37  149.39  693.13   171.5  692.16  188.34  691.91  191.39  692.19
  194.43  693.34  200.53  696.73  209.67  700.44  227.95  709.51     231  710.37
  234.04  710.52  261.47  720.26  279.75  726.03  285.84  727.13  288.89  728.38
#Mann= 3 , 0 , 0
       0      .1       0   171.5      .1       0  191.39      .1       0
Bank Sta=171.5,191.39
XS Rating Curve= 0 ,0
Exp/Cntr=0.3,0.1

Type RM Length L Ch R = 1 ,5486.4  ,90.86,91.44,89.39
XS GIS Cut Line= 6
     626055.4923    4341891.7369     625986.8219    4341975.6491
     625983.2698    4341983.7191     625979.0106    4341988.9804
     625974.5849    4341997.4772     625892.5086     4342078.004
#Sta/Elev= 30
       0  719.95   12.05  715.25   15.06  714.21   18.07  713.89    24.1  711.42
   42.17  705.32    51.2  703.38   54.21  702.19   57.23   700.5   63.25  698.79
   72.29  694.89   81.32  691.67   84.33  691.06   99.39  689.62  114.31  689.02
  117.25  689.07  120.71  689.66  126.41  691.18  136.62  691.99  139.65  692.61
  148.73   696.1   157.8  700.96  163.85  702.89  191.09  708.94  200.16  710.53
  206.22  712.09  218.32  713.12  230.42  715.01  245.55  718.94  248.58  719.24
#Mann= 3 , 0 , 0
       0      .1       0   99.39      .1       0  120.71      .1       0
Bank Sta=99.39,120.71
XS Rating Curve= 0 ,0
Exp/Cntr=0.3,0.1

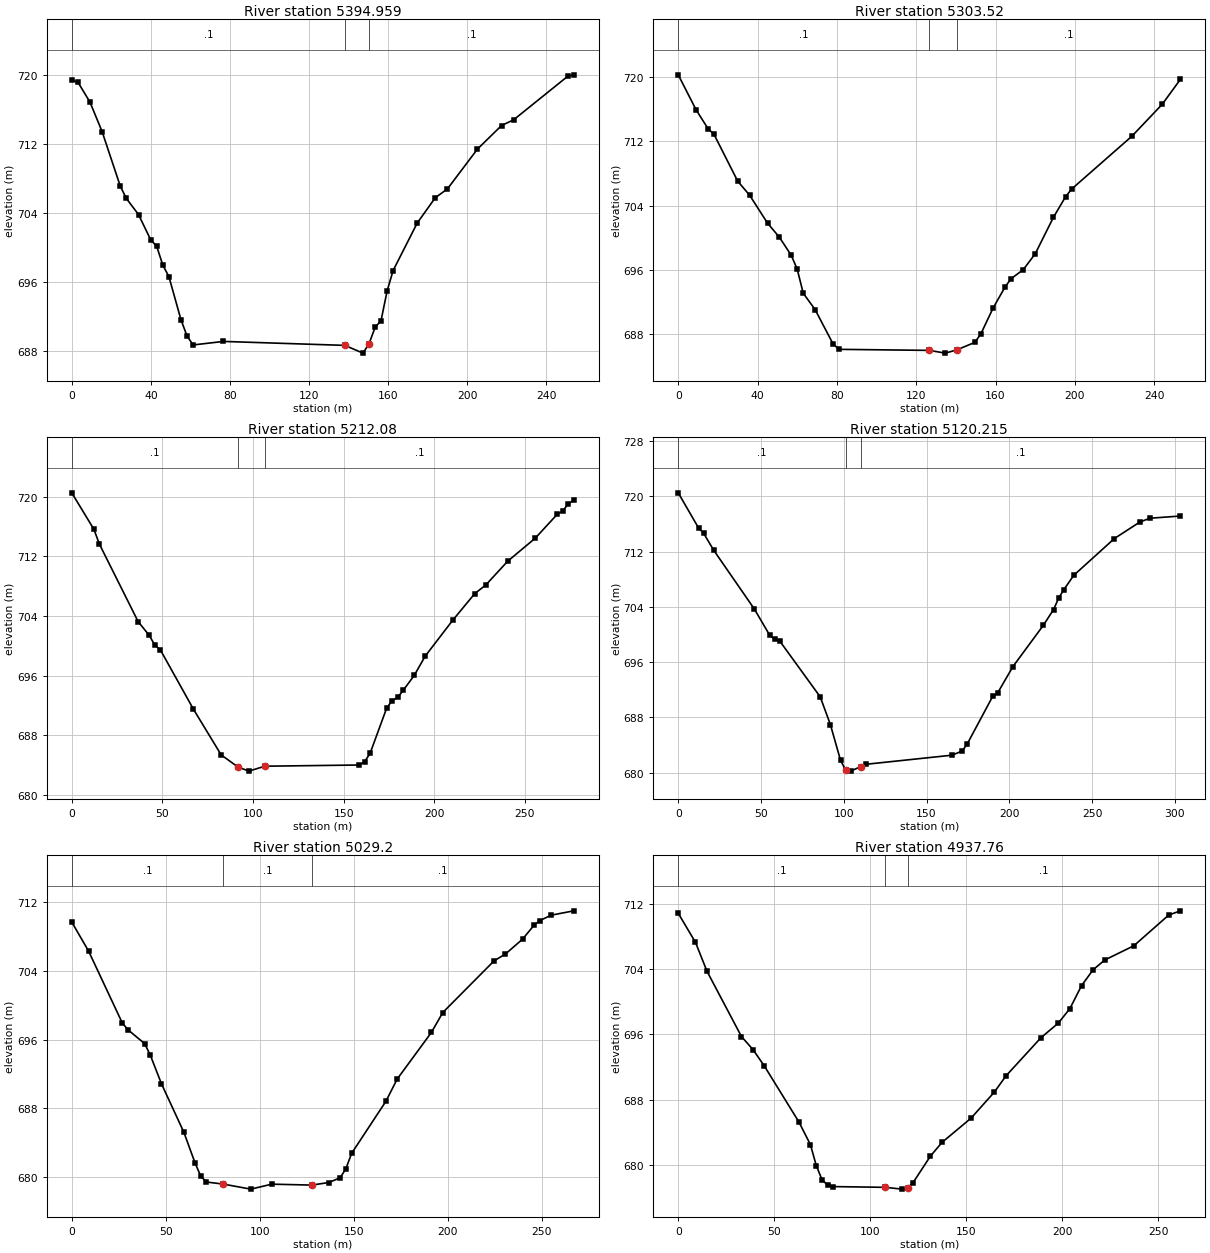
Type RM Length L Ch R = 1 ,5394.959,79.64,91.44,94.03
XS GIS Cut Line= 3
     625971.8838    4341822.9451     625898.9482    4341947.3283
     625861.8169    4342050.4872
#Sta/Elev= 30
       0  719.42    3.07  719.23     9.2   716.9   15.34  713.47   24.54  707.12
   27.61   705.7   33.75  703.83   39.88  700.91   42.95  700.14   46.02  697.96
   49.09  696.63   55.22   691.6   58.29  689.71   61.36  688.68    76.7  689.09
  138.05  688.63  147.24  687.73  150.32  688.84  153.33  690.71  156.37  691.52
  159.42  694.95  162.46  697.33  174.65  702.85  183.78  705.79  189.87   706.8
   205.1  711.44  217.28  714.18  223.37  714.84  250.78  719.91  253.83  720.07
#Mann= 3 , 0 , 0
       0      .1       0  138.05      .1       0  150.32      .1       0
Bank Sta=138.05,150.32
XS Rating Curve= 0 ,0
Exp/Cntr=0.3,0.1

Type RM Length L Ch R = 1 ,5303.52 ,87.25,91.44,80.62
XS GIS Cut Line= 4
     625935.9004    4341792.2534     625850.6152    4341872.4145
     625832.2115    4341886.9116       625751.75    4341965.8204
#Sta/Elev= 30
       0  720.23       9  715.89   15.01  713.55   18.01  712.85   30.01  707.02
   36.01  705.28   45.02  701.82   51.02  700.06   57.02  697.81   60.02  696.08
   63.02  693.12   69.03  691.08   78.03  686.84   81.03  686.15  126.66  686.02
  134.62  685.68  140.47  686.08  149.61  687.02  152.66   688.1  158.75  691.27
  164.84  693.91  167.88  694.93  173.98  696.04  180.07  698.04  189.21  702.55
   195.3  705.09  198.34  706.04   228.8  712.62  244.03  716.57  253.17  719.65
#Mann= 3 , 0 , 0
       0      .1       0  126.66      .1       0  140.47      .1       0
Bank Sta=126.66,140.47
XS Rating Curve= 0 ,0
Exp/Cntr=0.3,0.1

Type RM Length L Ch R = 1 ,5212.08 ,97.5,91.86,87.59
XS GIS Cut Line= 6
     625872.4003    4341724.5199     625806.9049    4341796.9778
      625805.769    4341805.7856     625792.0994    4341821.8983
     625785.7382    4341823.4362     625688.2499    4341927.7203
#Sta/Elev= 30
       0   720.5   12.21  715.61   15.26  713.62   36.63  703.24   42.73  701.41
   45.78  700.11   48.84  699.48   67.15   691.5   82.41   685.4   91.57  683.79
   97.67  683.22  106.55  683.88  158.53  684.04  161.56  684.48   164.6  685.62
  173.71  691.66  176.75  692.67  179.79  693.09  182.82  694.04   188.9  696.03
  194.97  698.62  210.16  703.43  222.31     707  228.39  708.15  240.53  711.35
  255.72  714.43  267.87  717.64  270.91  718.07  273.95  719.07  276.98  719.48
#Mann= 3 , 0 , 0
       0      .1       0   91.57      .1       0  106.55      .1       0
Bank Sta=91.57,106.55
XS Rating Curve= 0 ,0
Exp/Cntr=0.3,0.1

Type RM Length L Ch R = 1 ,5120.215,100.89,91.02,97.47
XS GIS Cut Line= 2
     625821.6002    4341656.7864     625624.7498    4341887.5036
#Sta/Elev= 30
       0  720.52   12.25  715.44   15.32  714.67   21.44   712.2   45.95   703.7
   55.14  699.94   58.21  699.29   61.27  699.07   85.78  690.96    91.9  686.96
   98.03  681.78  101.09  680.38  104.16  680.21  110.28  680.87  113.35   681.2
  165.43  682.52  171.55  683.13  174.62  684.17  189.93  691.03     193  691.56
  202.19  695.36  220.57  701.34   226.7  703.61  229.76  705.25  232.82  706.46
  238.95  708.58  263.46   713.9  278.78  716.28   284.9  716.84  303.28  717.16
#Mann= 3 , 0 , 0
       0      .1       0  101.09      .1       0  110.28      .1       0
Bank Sta=101.09,110.28
XS Rating Curve= 0 ,0
Exp/Cntr=0.3,0.1

Type RM Length L Ch R = 1 ,5029.2  ,86,91.44,87.32
XS GIS Cut Line= 6
     625736.9333     4341589.053     625694.7214    4341664.5006
      625693.353    4341670.3276     625685.2587    4341681.7256
     625664.9557    4341687.9163     625540.0829      4341749.92
#Sta/Elev= 30
       0  709.71    8.94  706.33   26.83  697.97   29.81  697.17   38.75  695.55
   41.74  694.22    47.7  690.87   59.62  685.22   65.59  681.63   68.57  680.12
   71.55  679.42   80.49  679.18   95.23  678.59  106.42  679.17  127.64  679.06
  136.74  679.36   142.8  679.92  145.83  680.98  148.86  682.76  167.05  688.81
  173.11  691.42  191.29  696.85  197.35  699.17  224.63  705.19  230.69  705.99
  239.79  707.72  245.85  709.33  248.88  709.87  254.94  710.51  267.06  711.02
#Mann= 3 , 0 , 0
       0      .1       0   80.49      .1       0  127.64      .1       0
Bank Sta=80.49,127.64
XS Rating Curve= 0 ,0
Exp/Cntr=0.3,0.1

Type RM Length L Ch R = 1 ,4937.76 ,90.28,91.71,93.51
XS GIS Cut Line= 4
      625716.137    4341539.0995     625629.3394    4341607.9298
     625620.8266    4341615.6318     625533.5742    4341724.0437
#Sta/Elev= 30
       0  710.82    8.98  707.26   14.97  703.72   32.93  695.72   38.92  694.13
   44.91  692.09   62.87  685.25   68.86  682.47   71.86  679.93   74.85   678.2
   77.84  677.51   80.84  677.35  107.78  677.26  116.52  677.04  119.39  677.15
  122.26  677.83  131.33  681.09  137.38  682.77  152.51  685.74  164.61  688.93
  170.66  690.91  188.81  695.57  197.89  697.37  203.94  699.15  209.99  701.96
  216.04  703.91  222.09   705.1  237.22  706.84  255.37   710.6  261.42  711.12
#Mann= 3 , 0 , 0
       0      .1       0  107.78      .1       0  119.39      .1       0
Bank Sta=107.78,119.39
XS Rating Curve= 0 ,0
Exp/Cntr=0.3,0.1

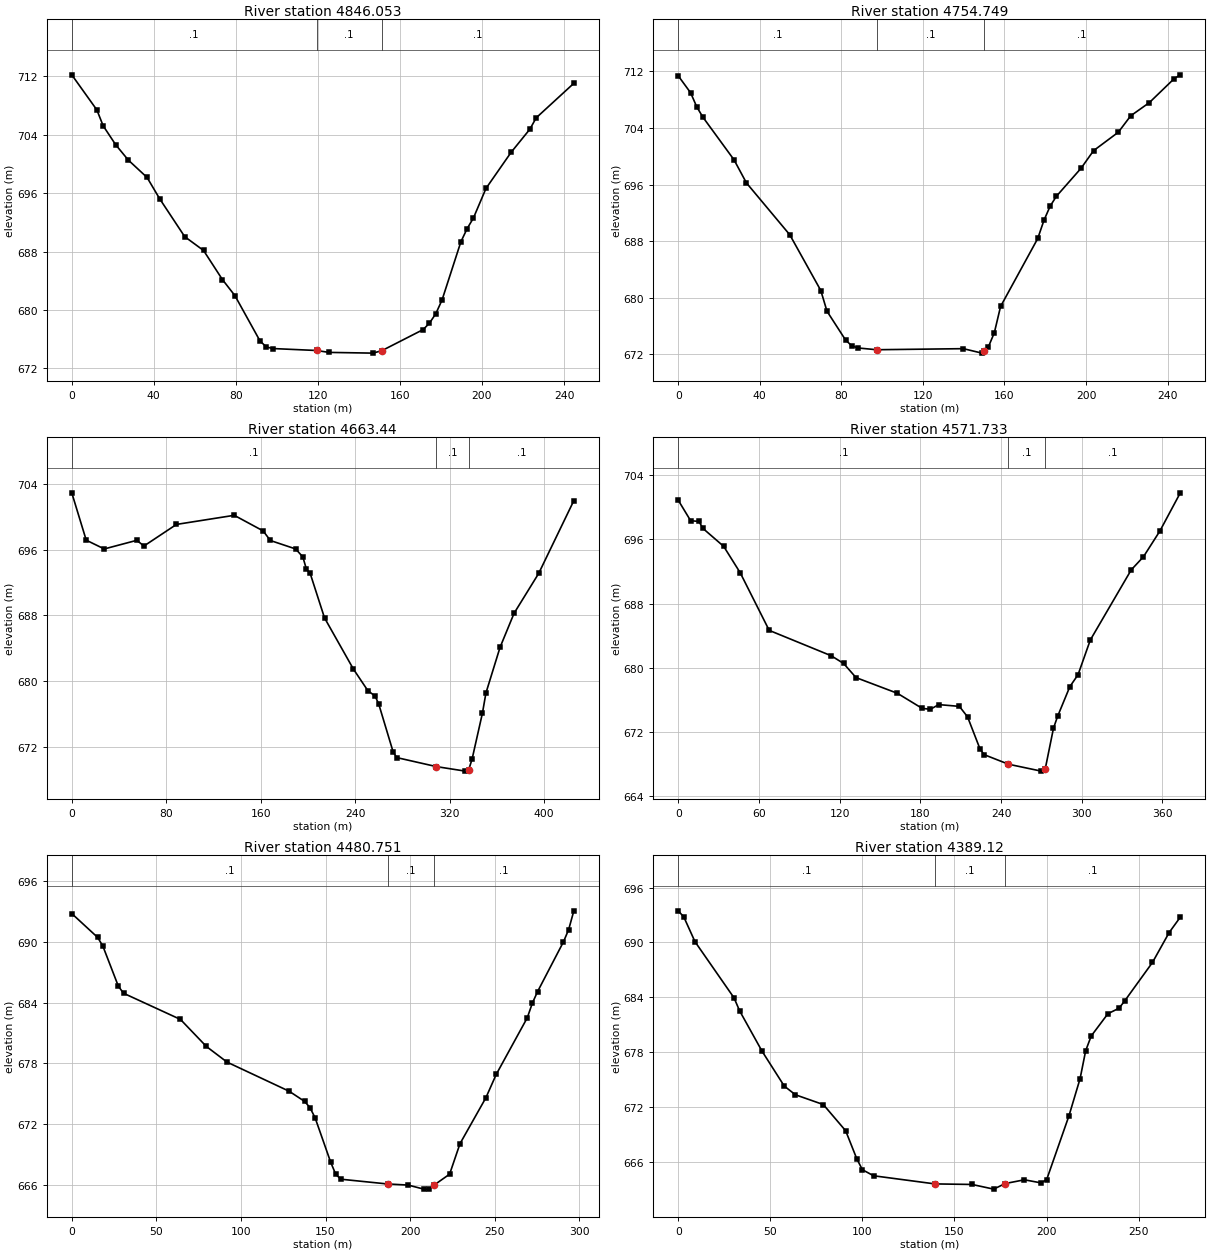
Type RM Length L Ch R = 1 ,4846.053,84.12,91.3,92.57
XS GIS Cut Line= 2
      625687.562    4341461.3119     625484.1166    4341597.4705
#Sta/Elev= 30
       0  712.21   12.24   707.4    15.3  705.23   21.42  702.63   27.54  700.54
   36.72  698.15   42.84  695.24   55.08  690.04   64.26  688.15   73.44  684.17
   79.56  681.96    91.8  675.75   94.86  674.94   97.92  674.72  119.34  674.45
  125.46  674.19  146.88  674.09  151.21  674.43  171.36  677.32  174.42  678.21
  177.48  679.48  180.54  681.37  189.72  689.34  192.78  691.15  195.84   692.6
  201.96  696.65   214.2  701.59  223.38  704.77  226.44  706.32   244.8  711.05
#Mann= 3 , 0 , 0
       0      .1       0  119.34      .1       0  151.21      .1       0
Bank Sta=119.34,151.21
XS Rating Curve= 0 ,0
Exp/Cntr=0.3,0.1

Type RM Length L Ch R = 1 ,4754.749,104.98,91.31,85.1
XS GIS Cut Line= 2
     625668.5119    4341428.7681      625428.799    4341485.1244
#Sta/Elev= 30
       0  711.38    6.08  708.98    9.12  706.97   12.16  705.51   27.36  699.51
   33.44  696.25   54.72  688.91   69.92  681.04   72.96  678.11   82.08  674.04
   85.12  673.22   88.16  672.92   97.28  672.67  139.84  672.82  148.97  672.19
  150.01  672.47  152.01  672.99  155.05  675.09  158.09  678.78  176.33  688.39
  179.37  690.96  182.41  692.96  185.45  694.35  197.61  698.33  203.69   700.8
  215.85  703.41  221.93  705.73  231.05  707.59  243.21  710.97  246.25  711.52
#Mann= 3 , 0 , 0
       0      .1       0   97.28      .1       0  150.01      .1       0
Bank Sta=97.28,150.01
XS Rating Curve= 0 ,0
Exp/Cntr=0.3,0.1

Type RM Length L Ch R = 1 ,4663.44 ,86.41,91.71,92.36
XS GIS Cut Line= 5
     625727.6464    4341131.3758     625520.1566    4341372.5048
     625516.6463    4341381.3045     625507.2943    4341395.9045
     625435.9427    4341433.0014
#Sta/Elev= 30
       0  702.92   12.24  697.15   27.53  696.08   55.06  697.13   61.18  696.44
    88.7  699.07  137.64  700.18  162.11  698.28  168.23  697.11  189.64  696.08
  195.76  695.11  198.82  693.59  201.88  693.14  214.11  687.68  238.58  681.44
  250.82  678.81  256.94  678.15     260   677.2  272.23  671.35  275.29  670.65
  308.94  669.55  333.37     669  336.26  669.17  339.14  670.47   347.9  676.07
  350.88  678.53   362.8  684.08  374.71  688.24  395.56   693.1  425.34  701.97
#Mann= 3 , 0 , 0
       0      .1       0  308.94      .1       0  336.26      .1       0
Bank Sta=308.94,336.26
XS Rating Curve= 0 ,0
Exp/Cntr=0.3,0.1

Type RM Length L Ch R = 1 ,4571.733,83.83,90.98,92.34
XS GIS Cut Line= 3
     625662.8234     4341144.605     625498.9739    4341274.4174
     625379.7187    4341387.3607
#Sta/Elev= 30
       0  700.86    9.22  698.31   15.37  698.22   18.44  697.34   33.82  695.11
   46.11  691.82   67.63  684.66  113.74   681.5  122.96  680.54  132.19  678.78
  162.93  676.83  181.37  674.95  187.52  674.84  193.67  675.42  209.04   675.2
  215.12  673.89  224.25  669.95  227.29   669.2  245.54     668  269.87  667.14
  272.92  667.46     279  672.49  282.04  673.95  291.17  677.66  297.25  679.14
  306.37  683.46  336.79  692.19  345.92  693.83  358.08  697.02  373.29  701.78
#Mann= 3 , 0 , 0
       0      .1       0  245.54      .1       0  272.92      .1       0
Bank Sta=245.54,272.92
XS Rating Curve= 0 ,0
Exp/Cntr=0.3,0.1

Type RM Length L Ch R = 1 ,4480.751,57.67,91.63,101.82
XS GIS Cut Line= 2
     625589.4014    4341169.7405     625314.2342    4341280.8657
#Sta/Elev= 30
       0  692.82    15.3  690.46   18.36  689.61   27.53  685.64   30.59  684.94
   64.25  682.35   79.54  679.68   91.78  678.13  128.49  675.25  137.67  674.24
  140.73  673.64  143.79  672.64  152.97  668.26  156.03  667.03  159.09  666.55
  186.62  666.08  198.86  665.97  208.04  665.57   211.1  665.58  214.16  665.97
  223.33  667.05  229.45  670.06  244.75   674.6  250.87  676.91  269.22  682.51
  272.28  683.98  275.34  685.11  290.64  690.03   293.7  691.24  296.76  693.09
#Mann= 3 , 0 , 0
       0      .1       0  186.62      .1       0  214.16      .1       0
Bank Sta=186.62,214.16
XS Rating Curve= 0 ,0
Exp/Cntr=0.3,0.1

Type RM Length L Ch R = 1 ,4389.12 ,124.23,91.44,61.89
XS GIS Cut Line= 6
     625502.0887    4341141.2977     625373.6673    4341202.8991
     625357.0373    4341187.2642      625356.743    4341181.2272
     625345.0816    4341176.0239     625258.0101     4341186.277
#Sta/Elev= 30
       0  693.46    3.03  692.79    9.09  690.09    30.3  683.95   33.34  682.53
   45.46  678.14   57.58  674.31   63.64  673.36   78.79  672.29   90.91  669.43
   96.97  666.36  100.01  665.17  106.07  664.51   139.4  663.62  159.55  663.56
   171.3  663.05  177.56  663.66     188  664.07  197.07  663.73  200.09   664.1
  212.18  671.06  218.23  675.13  221.25  678.17  224.28  679.79  233.35  682.22
  239.39  682.82  242.42  683.61  257.53  687.82   266.6  691.09  272.65  692.77
#Mann= 3 , 0 , 0
       0      .1       0   139.4      .1       0  177.56      .1       0
Bank Sta=139.4,177.56
XS Rating Curve= 0 ,0
Exp/Cntr=0.3,0.1