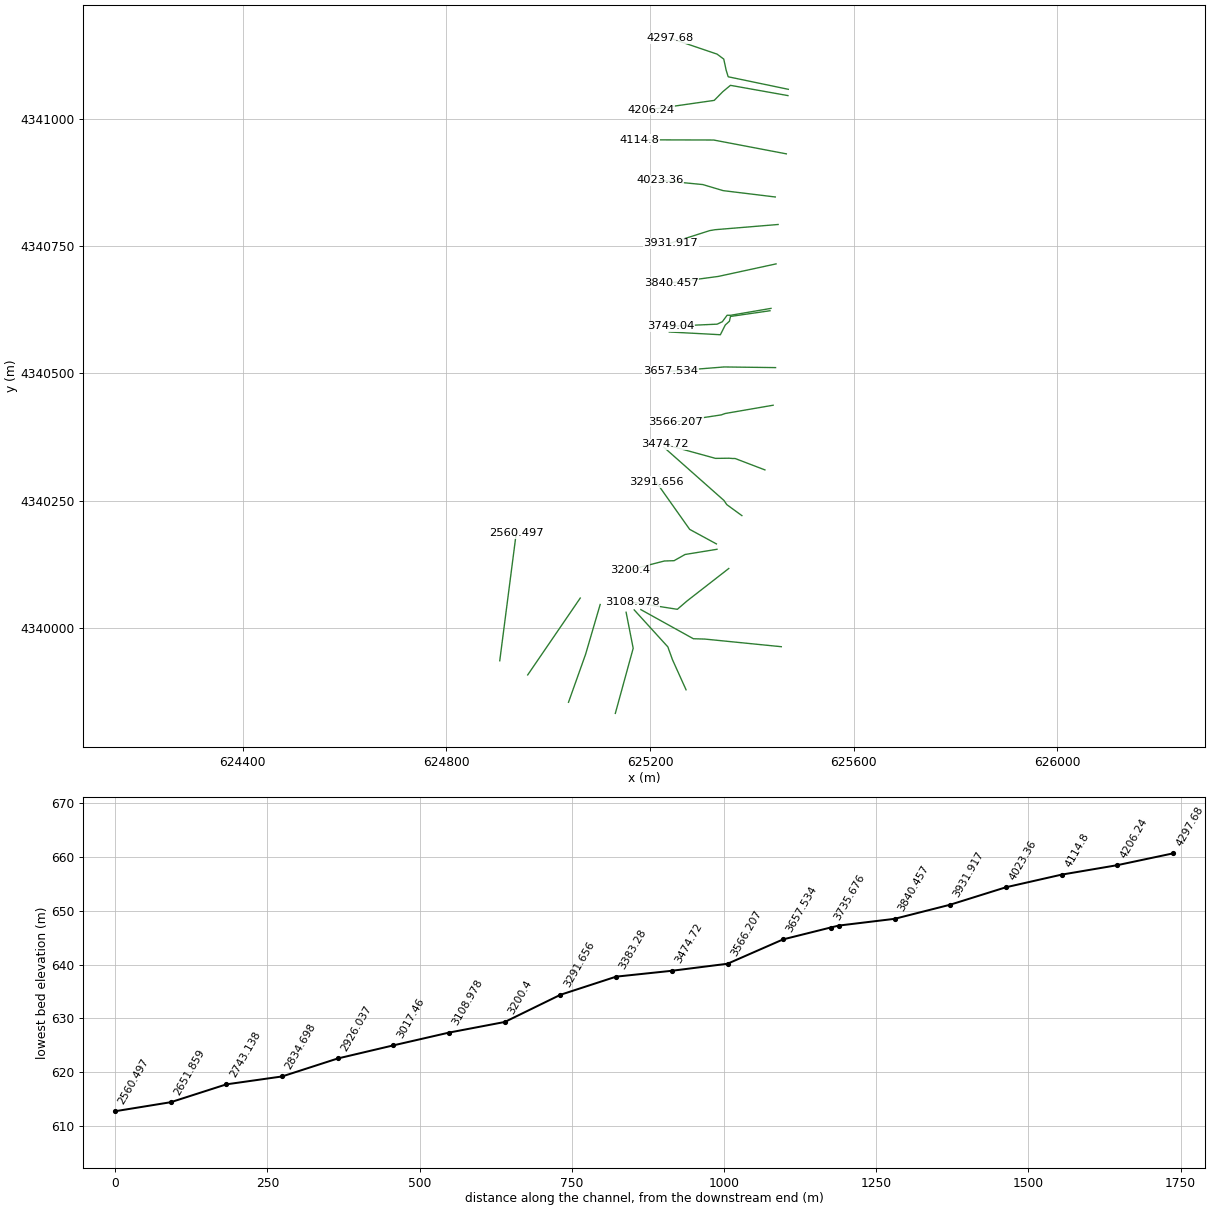
HEC-RAS study LeadmineRun.prj: LeadmineRun

--- LeadmineRun.g01 (geometry) --- (continued)

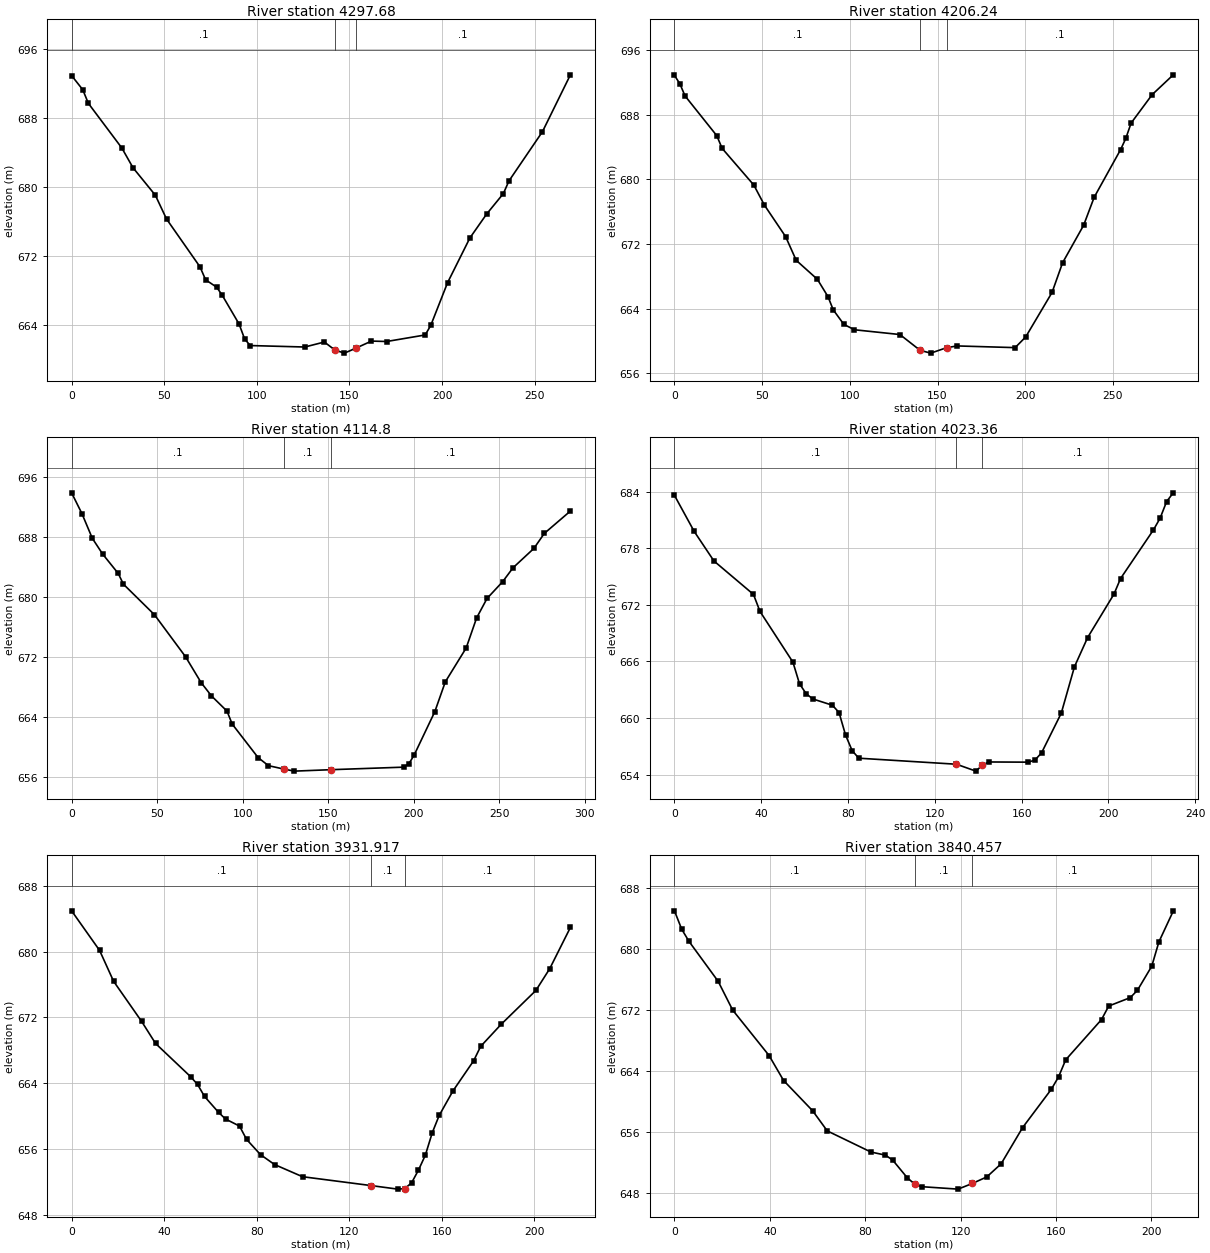
Type RM Length L Ch R = 1 ,4297.68 ,41.49,91.44,104.43
XS GIS Cut Line= 6
     625471.3639    4341057.5238     625353.3365    4341082.1075
     625349.3678    4341094.8075     625344.6207    4341116.7894
     625331.5083    4341126.5575     625240.1176    4341157.5365
#Sta/Elev= 30
       0  692.91    6.03  691.27    9.04  689.69   27.13   684.5   33.15  682.21
   45.21  679.02   51.24  676.26   69.32   670.7   72.34   669.2   78.36  668.33
   81.38  667.38   90.42  664.06   93.43  662.32   96.45  661.56  125.88  661.39
  136.47  661.97  142.21  661.03  147.32  660.68  153.41  661.25  161.91  662.08
  170.09  662.03  190.91  662.79  193.92   663.9  202.97  668.85  215.03  674.05
  224.08  676.83  233.12  679.21  236.14  680.68  254.23   686.4  269.31     693
#Mann= 3 , 0 , 0
       0      .1       0  142.21      .1       0  153.41      .1       0
Bank Sta=142.21,153.41
XS Rating Curve= 0 ,0
Exp/Cntr=0.3,0.1

Type RM Length L Ch R = 1 ,4206.24 ,108.09,91.44,77.73
XS GIS Cut Line= 5
     625470.6583    4341045.1766     625357.7604    4341065.2958
      625342.833    4341052.9215     625325.8842    4341035.7872
     625200.9592    4341017.8363
#Sta/Elev= 30
       0  692.84    3.02  691.83    6.04   690.3   24.14  685.38   27.16  683.82
   45.27  679.27    51.3  676.79   63.37   672.9   69.41  669.97   81.48  667.62
   87.52  665.48   90.53  663.84   96.57  662.05  102.61  661.38  128.53  660.79
  140.09  658.83  146.12  658.49  155.15  659.16  161.17  659.38  194.23  659.17
  200.24  660.49  215.26  665.99  221.27  669.66  233.29  674.31   239.3  677.77
  254.33  683.65  257.33  685.05  260.34  686.94  272.35  690.46  284.37  692.91
#Mann= 3 , 0 , 0
       0      .1       0  140.09      .1       0  155.15      .1       0
Bank Sta=140.09,155.15
XS Rating Curve= 0 ,0
Exp/Cntr=0.3,0.1

Type RM Length L Ch R = 1 ,4114.8  ,92.96,91.44,88.95
XS GIS Cut Line= 3
     625467.4833    4340930.8764     625324.7466    4340958.0021
     625178.5578    4340958.3931
#Sta/Elev= 30
       0  693.84    6.05  691.06   12.11  687.77   18.16  685.67   27.24  683.09
   30.27  681.66   48.43  677.58   66.59  671.98   75.67  668.54   81.73  666.76
   90.81  664.73   93.83  663.01  108.97  658.54  115.02  657.46   124.1     657
  130.16  656.73  151.38  656.92  194.02  657.26  197.07  657.71  200.11  658.84
  212.29  664.68  218.39  668.64  230.57  673.15  236.66  677.15  242.75  679.75
  251.89  681.99  257.98  683.85  270.16  686.43  276.25  688.43  291.48  691.41
#Mann= 3 , 0 , 0
       0      .1       0   124.1      .1       0  151.38      .1       0
Bank Sta=124.1,151.38
XS Rating Curve= 0 ,0
Exp/Cntr=0.3,0.1

Type RM Length L Ch R = 1 ,4023.36 ,81.44,91.44,102.35
XS GIS Cut Line= 4
     625445.8404    4340846.2095     625343.4436     4340858.669
     625303.4296    4340870.5898     625218.8274    4340878.7533
#Sta/Elev= 30
       0  683.59     9.1  679.77    18.2  676.64   36.41   673.1   39.44  671.29
   54.61  665.92   57.64  663.63   60.68  662.59   63.71  662.03   72.81  661.36
   75.85  660.59   78.88  658.19   81.91  656.55   84.95  655.75  129.99  655.11
  138.94  654.38  141.92  655.02   144.9  655.35  163.12  655.33  166.15  655.55
  169.19  656.31  178.29  660.52  184.37  665.44  190.44  668.53  202.58  673.13
  205.61  674.78  220.79  679.94  223.83  681.17  226.86  682.94   229.9  683.86
#Mann= 3 , 0 , 0
       0      .1       0  129.99      .1       0  141.92      .1       0
Bank Sta=129.99,141.92
XS Rating Curve= 0 ,0
Exp/Cntr=0.3,0.1

Type RM Length L Ch R = 1 ,3931.917,92.02,91.46,91.55
XS GIS Cut Line= 4
     625451.3966    4340792.2344     625327.8596    4340782.0222
     625317.0166     4340780.222     625240.2587    4340755.7218
#Sta/Elev= 30
       0  684.96   12.09  680.15   18.14   676.4   30.23  671.53   36.28  668.84
    51.4  664.81   54.42  663.86   57.44   662.4   63.49  660.47   66.51  659.66
   72.56   658.8   75.58  657.19   81.63  655.33   87.68  654.13   99.77  652.65
  129.45  651.57  140.92  651.14   143.9   651.2  146.89   651.9  149.87  653.45
  152.85  655.27  155.84     658  158.82  660.09  164.79  663.08  173.74  666.75
  176.73  668.48  185.68  671.19   200.6  675.28  206.57  677.92  215.52  682.94
#Mann= 3 , 0 , 0
       0      .1       0  129.45      .1       0   143.9      .1       0
Bank Sta=129.45,143.9
XS Rating Curve= 0 ,0
Exp/Cntr=0.3,0.1

Type RM Length L Ch R = 1 ,3840.457,85.22,91.42,92.99
XS GIS Cut Line= 3
     625447.2956    4340714.9098     625333.9826    4340690.3431
     625241.5816     4340677.868
#Sta/Elev= 30
       0  685.02    3.05   682.6     6.1  681.01   18.31  675.78   24.41     672
   39.67  666.04   45.77  662.76   57.97  658.78   64.08  656.15   82.38  653.38
   88.48  652.97   91.54  652.31   97.64     650  100.69  649.18  103.74  648.83
  118.95  648.51  124.97  649.26  130.98  650.11     137  651.83  146.02  656.59
  158.05  661.61  161.06  663.22  164.07  665.47  179.11  670.76  182.12  672.53
  191.14  673.63  194.15  674.59  200.16  677.75  203.17  680.95  209.18  684.99
#Mann= 3 , 0 , 0
       0      .1       0  100.69      .1       0  124.97      .1       0
Bank Sta=100.69,124.97
XS Rating Curve= 0 ,0
Exp/Cntr=0.3,0.1

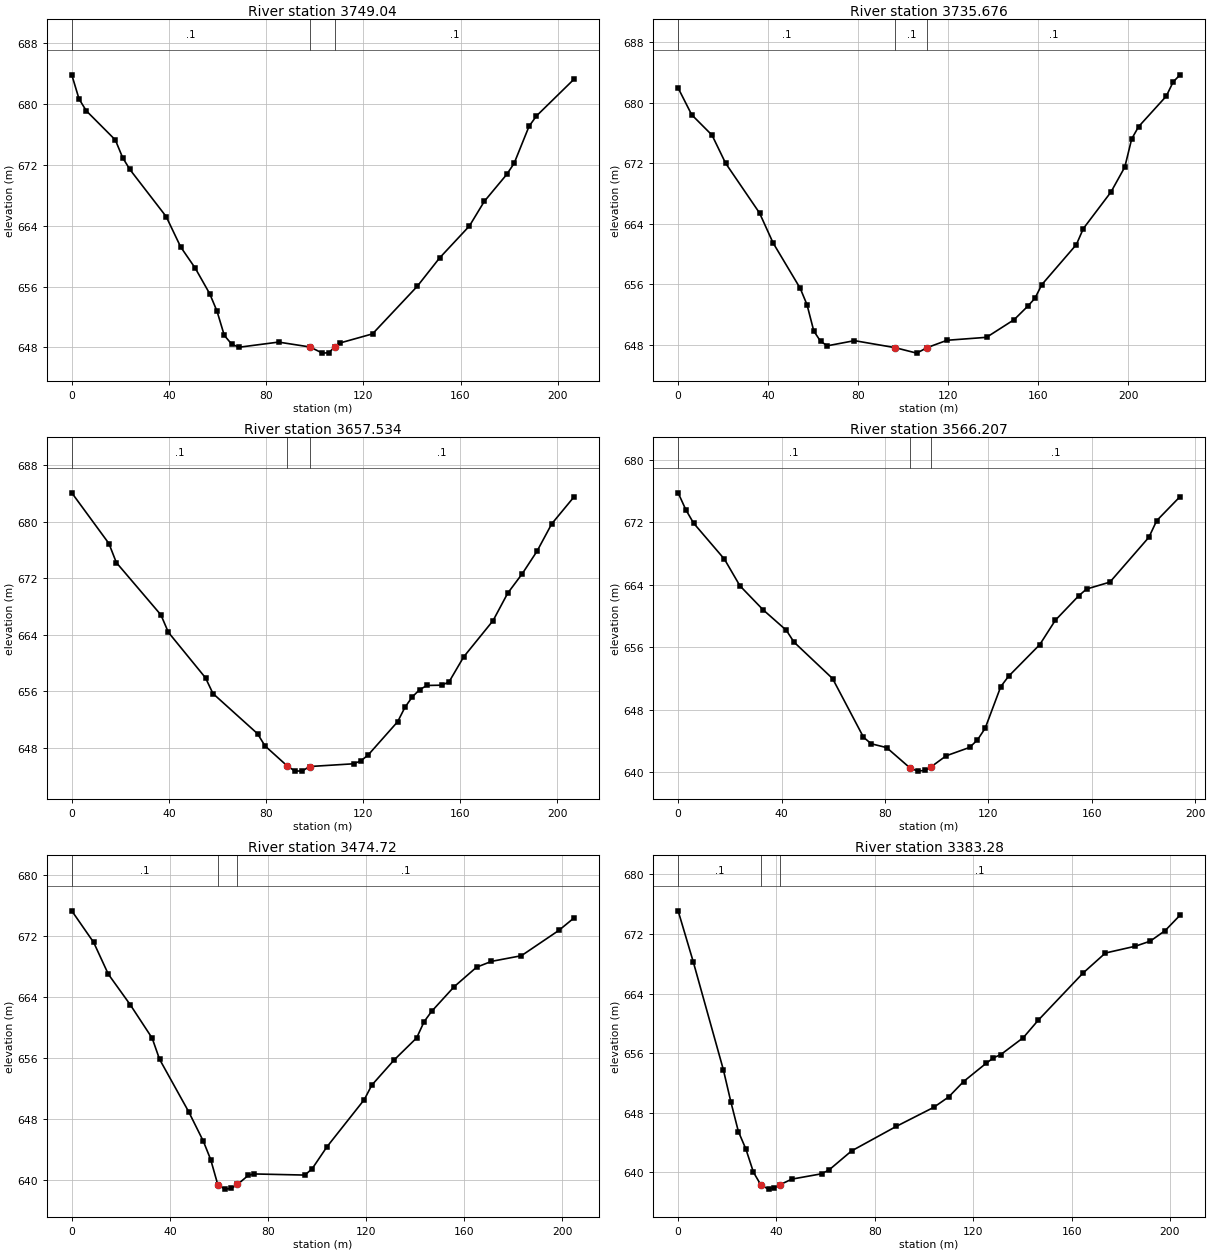
Type RM Length L Ch R = 1 ,3749.04 ,12.83,13.36,19.54
XS GIS Cut Line= 6
     625437.3737    4340627.5971     625357.8305    4340614.0273
     625351.2159    4340614.1596      625341.824    4340601.4148
     625331.5242    4340596.6384     625239.5973    4340592.5398
#Sta/Elev= 30
       0  683.84    2.99  680.67    5.98  679.11   17.93  675.28   20.92  672.97
   23.91   671.4   38.85  665.21   44.83  661.21   50.81  658.43   56.78  655.06
   59.77  652.78   62.76   649.6   65.75  648.46   68.74  648.03    85.1  648.71
      98  648.07  103.16  647.26  105.77  647.31  108.39  648.13  110.45   648.6
  123.77  649.79  142.17  656.04  151.37  659.77  163.64  663.97  169.78  667.21
  178.98  670.74  182.05  672.21  188.18  677.07  191.25  678.44  206.58  683.23
#Mann= 3 , 0 , 0
       0      .1       0      98      .1       0  108.39      .1       0
Bank Sta=98,108.39
XS Rating Curve= 0 ,0
Exp/Cntr=0.3,0.1

Type RM Length L Ch R = 1 ,3735.676,90.33,78.14,66.55
XS GIS Cut Line= 6
     625435.3893    4340622.9669     625357.8159    4340611.7809
     625355.7522    4340602.4147     625347.5765    4340594.9534
     625337.9721    4340575.9034     625237.6129    4340581.2949
#Sta/Elev= 30
       0  681.97    6.03  678.43   15.07  675.73    21.1  672.02   36.17  665.44
    42.2  661.48   54.26  655.47   57.27  653.31   60.29  649.83    63.3  648.46
   66.32  647.87   78.38  648.55   96.49  647.62  106.02   646.9  110.77  647.64
  119.51   648.6  137.05  648.99  149.34  651.33  155.49  653.14  158.56  654.15
  161.63  655.96  176.99  661.26  180.07  663.37  192.36  668.21   198.5  671.51
  201.57  675.24  204.65  676.86  216.94  680.89  220.01  682.78  223.08  683.71
#Mann= 3 , 0 , 0
       0      .1       0   96.49      .1       0  110.77      .1       0
Bank Sta=96.49,110.77
XS Rating Curve= 0 ,0
Exp/Cntr=0.3,0.1

Type RM Length L Ch R = 1 ,3657.534,92.44,91.33,93.71
XS GIS Cut Line= 3
     625446.3695    4340511.3897     625345.4033    4340512.6675
     625239.9941    4340504.2459
#Sta/Elev= 30
       0   684.1    15.3  676.92   18.36  674.22   36.72  666.81   39.78  664.35
   55.08   657.9   58.14  655.68    76.5  649.99   79.56  648.27   88.74  645.42
   91.79  644.72   94.85  644.69   97.91  645.34  116.08  645.73   119.1  646.15
  122.12     647  134.21  651.69  137.23  653.74  140.25  655.21  143.27  656.23
  146.29  656.82  152.34  656.86  155.36  657.32   161.4  660.87  173.49     666
  179.53  669.89  185.57  672.67  191.61  675.84  197.66  679.71  206.72  683.48
#Mann= 3 , 0 , 0
       0      .1       0   88.74      .1       0   97.91      .1       0
Bank Sta=88.74,97.91
XS Rating Curve= 0 ,0
Exp/Cntr=0.3,0.1

Type RM Length L Ch R = 1 ,3566.207,98,91.49,86.77
XS GIS Cut Line= 4
      625441.607    4340437.5708      625347.398    4340421.3298
     625339.7814    4340418.5977     625250.3129     4340405.027
#Sta/Elev= 30
       0  675.76    2.99  673.59    5.97  671.89   17.92  667.27    23.9  663.87
   32.86   660.8   41.82  658.19   44.81  656.67   59.75     652    71.7   644.5
   74.69  643.66   80.66  643.17   89.62  640.59   92.61  640.16    95.6  640.26
   97.85  640.71  103.69  642.12  112.74  643.19  115.76  644.14  118.77  645.64
  124.81  650.97  127.82  652.29  139.89  656.34  145.92  659.46  154.97  662.59
  157.99  663.45  167.03  664.34  182.12  670.08  185.13   672.2  194.18  675.28
#Mann= 3 , 0 , 0
       0      .1       0   89.62      .1       0   97.85      .1       0
Bank Sta=89.62,97.85
XS Rating Curve= 0 ,0
Exp/Cntr=0.3,0.1

Type RM Length L Ch R = 1 ,3474.72 ,93.2,91.44,79.51
XS GIS Cut Line= 6
     625425.4145    4340310.6764     625366.9233    4340333.0049
     625361.9624    4340333.0049     625355.3803    4340333.5769
     625328.5628    4340333.2458     625228.5641    4340360.6827
#Sta/Elev= 30
       0   675.3    8.94  671.16   14.91     667   23.85     663   32.79  658.62
   35.78  655.87    47.7  648.97   53.66  645.12   56.65  642.72   59.63  639.34
   62.61  638.85   65.09  638.95   67.57  639.46   71.97  640.65   74.18  640.84
   95.04  640.69   98.02  641.52  104.05  644.39  119.29  650.58  122.34  652.47
  131.49  655.78  140.64  658.66  143.69  660.79  146.74  662.13  155.89  665.35
  165.04  667.91  171.14  668.68  183.34  669.42  198.59  672.73  204.69  674.34
#Mann= 3 , 0 , 0
       0      .1       0   59.63      .1       0   67.57      .1       0
Bank Sta=59.63,67.57
XS Rating Curve= 0 ,0
Exp/Cntr=0.3,0.1

Type RM Length L Ch R = 1 ,3383.28 ,98.24,91.62,87.06
XS GIS Cut Line= 4
     625380.1707    4340220.9824     625350.4598    4340242.6041
     625345.2294    4340250.4945     625226.9766    4340355.1264
#Sta/Elev= 30
       0   675.1    6.12   668.3   18.37  653.81   21.43  649.49    24.5  645.49
   27.56  643.13   30.62  640.03   33.68   638.3   36.75  637.76   39.11  637.94
   41.48  638.36   46.21   639.1   58.36  639.82   61.39  640.34    70.5  642.88
   88.72  646.18  103.91  648.73  109.98  650.12  116.05  652.19  125.16  654.62
   128.2  655.37  131.23  655.82  140.34  658.08  146.42  660.42  164.64  666.75
  173.74  669.44  185.89  670.35  191.96  671.03  198.04  672.45  204.11  674.52
#Mann= 3 , 0 , 0
       0      .1       0   33.68      .1       0   41.48      .1       0
Bank Sta=33.68,41.48
XS Rating Curve= 0 ,0
Exp/Cntr=0.3,0.1

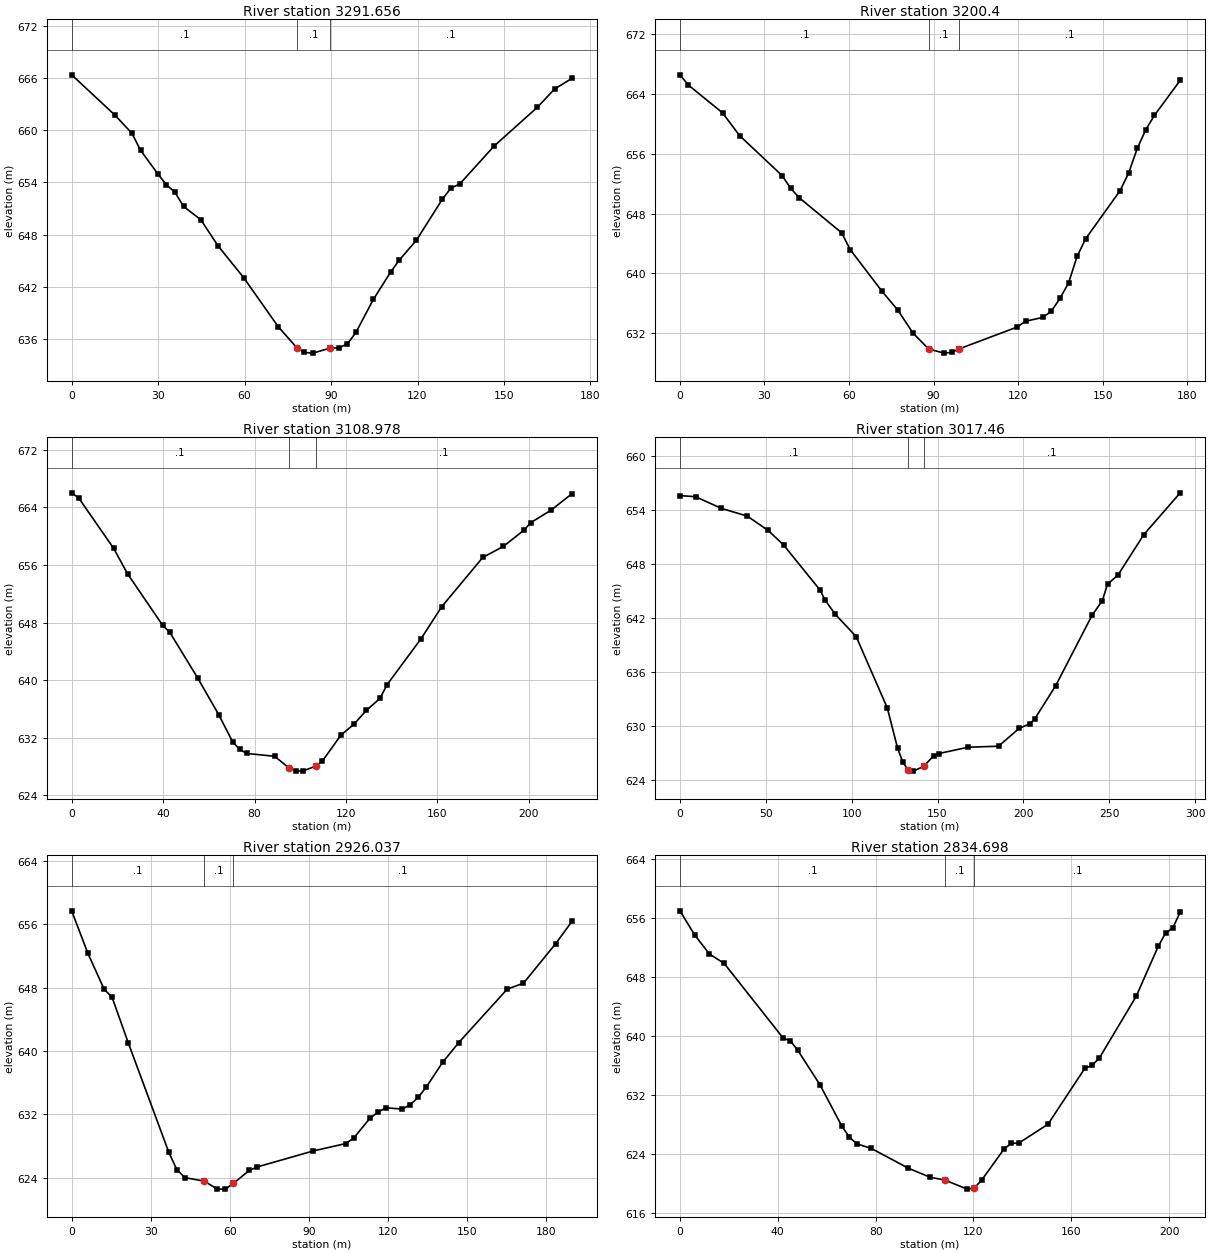
Type RM Length L Ch R = 1 ,3291.656,81.45,91.26,99.98
XS GIS Cut Line= 3
     625330.1643    4340165.4198     625277.6856    4340193.9319
     625211.8953    4340286.8638
#Sta/Elev= 30
       0  666.38   14.93  661.77    20.9  659.66   23.89  657.71   29.86  655.01
   32.85  653.75   35.83  652.88   38.82  651.24   44.79  649.73   50.77  646.72
   59.72  643.04   71.71   637.4   78.27  634.95    80.7  634.46    83.7  634.38
   89.69  634.96   92.68  634.99   95.68  635.43   98.68  636.79  104.67  640.55
  110.66  643.69  113.66  645.07  119.65  647.37  128.64  652.09  131.64  653.37
  134.63  653.82  146.62   658.2   161.6  662.65  167.59  664.76  173.59  665.97
#Mann= 3 , 0 , 0
       0      .1       0   78.27      .1       0   89.69      .1       0
Bank Sta=78.27,89.69
XS Rating Curve= 0 ,0
Exp/Cntr=0.3,0.1

Type RM Length L Ch R = 1 ,3200.4  ,88.6,91.42,95.53
XS GIS Cut Line= 5
     625331.2888    4340154.8629     625268.6794    4340144.6815
     625247.0764    4340132.5206     625227.9273    4340131.8714
     625159.9707    4340114.5139
#Sta/Elev= 30
       0  666.56    3.02  665.18    15.1  661.48   21.14  658.44   36.25  653.08
   39.27   651.4   42.29  650.13   57.39  645.42   60.41  643.18    71.7   637.6
    77.2  635.14   82.71  632.01   88.22  629.89    93.7  629.33   96.43  629.43
   99.17  629.91  119.58  632.81  122.63   633.6  128.73   634.1  131.78  634.93
  134.83  636.64  137.88  638.69  140.93  642.27  143.98  644.64  156.17  651.06
  159.22  653.42  162.27  656.71  165.32  659.23  168.37  661.14  177.52  665.82
#Mann= 3 , 0 , 0
       0      .1       0   88.22      .1       0   99.17      .1       0
Bank Sta=88.22,99.17
XS Rating Curve= 0 ,0
Exp/Cntr=0.3,0.1

Type RM Length L Ch R = 1 ,3108.978,96.15,91.52,83.63
XS GIS Cut Line= 4
     625354.4399    4340117.1597     625272.2453    4340053.2714
     625253.4554    4340037.0816      625164.601    4340051.0138
#Sta/Elev= 30
       0  666.03    3.06  665.32   18.37  658.31    24.5  654.75    39.8  647.62
   42.87  646.67   55.11  640.31    64.3  635.22   70.42  631.43   73.49  630.38
   76.55  629.82   88.79  629.42   94.92  627.84   97.98  627.43  101.04  627.36
  106.86  628.07  109.62  628.74  117.88   632.4   123.4  633.85  128.91   635.8
   134.9  637.47   137.9  639.34  152.89  645.78  161.88  650.21  179.87  657.06
  188.87  658.59  197.86  660.84  200.86  661.89  209.85  663.65  218.85  665.91
#Mann= 3 , 0 , 0
       0      .1       0   94.92      .1       0  106.86      .1       0
Bank Sta=94.92,106.86
XS Rating Curve= 0 ,0
Exp/Cntr=0.3,0.1

Type RM Length L Ch R = 1 ,3017.46 ,95.28,91.42,67.63
XS GIS Cut Line= 4
     625457.6276    4339963.7011     625307.4397    4339978.6793
     625284.9376      4339979.34     625181.7989    4340036.4616
#Sta/Elev= 30
       0  655.62    9.06   655.5   24.15   654.2   39.24  653.34   51.32  651.75
   60.37  650.13    81.5  645.14   84.52     644   90.56   642.4  102.63  639.94
  120.75  632.01  126.78  627.51   129.8  625.98  132.82  625.13  135.84  624.98
  141.88   625.5  147.91  626.71  150.93  626.94  167.82  627.64  185.54  627.75
  197.63  629.75  203.68  630.22   206.7  630.81  218.79  634.47  239.95  642.29
     246  643.94  249.02  645.78  255.07  646.78  270.18  651.29  291.35  655.93
#Mann= 3 , 0 , 0
       0      .1       0  132.82      .1       0  141.88      .1       0
Bank Sta=132.82,141.88
XS Rating Curve= 0 ,0
Exp/Cntr=0.3,0.1

Type RM Length L Ch R = 1 ,2926.037,94.15,91.34,79.53
XS GIS Cut Line= 4
     625270.5668    4339879.1665      625244.026    4339937.8512
     625234.7827    4339963.3877      625168.702    4340035.9325
#Sta/Elev= 30
       0   657.7    6.13  652.34   12.27  647.82   15.34  646.75   21.47  641.01
    36.8  627.22   39.87     625   42.94  623.99   50.25  623.55   55.21  622.55
   58.27  622.54   61.34  623.27   67.42  624.92   70.44  625.35   91.57  627.36
  103.83  628.29   106.9  628.97  113.03  631.47   116.1  632.25  119.16  632.82
   125.3  632.65  128.36  633.19  131.43  634.16   134.5  635.45  140.63  638.55
  146.76  641.05  165.16  647.81   171.3  648.55  183.56  653.57  189.69  656.36
#Mann= 3 , 0 , 0
       0      .1       0   50.25      .1       0   61.34      .1       0
Bank Sta=50.25,61.34
XS Rating Curve= 0 ,0
Exp/Cntr=0.3,0.1

Type RM Length L Ch R = 1 ,2834.698,91.36,91.56,88.8
XS GIS Cut Line= 3
     625131.6603    4339832.8644     625166.7401    4339960.5795
      625152.827    4340031.3023
#Sta/Elev= 30
       0  657.02    6.02  653.74   12.04  651.15   18.06  649.88   42.14  639.75
   45.15  639.34   48.16  638.07   57.19  633.41   66.22  627.74   69.23  626.29
   72.24  625.36   78.26  624.73   93.31  622.05  102.34  620.81  108.36  620.43
  117.39   619.2   120.4  619.37  123.41  620.45  132.45  624.63  135.45  625.43
  138.45  625.44  150.46  628.02  165.48   635.6  168.48  636.02  171.49  637.03
   186.5  645.39  195.51  652.18  198.52     654  201.52  654.71  204.52  656.85
#Mann= 3 , 0 , 0
       0      .1       0  108.36      .1       0   120.4      .1       0
Bank Sta=108.36,120.4
XS Rating Curve= 0 ,0
Exp/Cntr=0.3,0.1

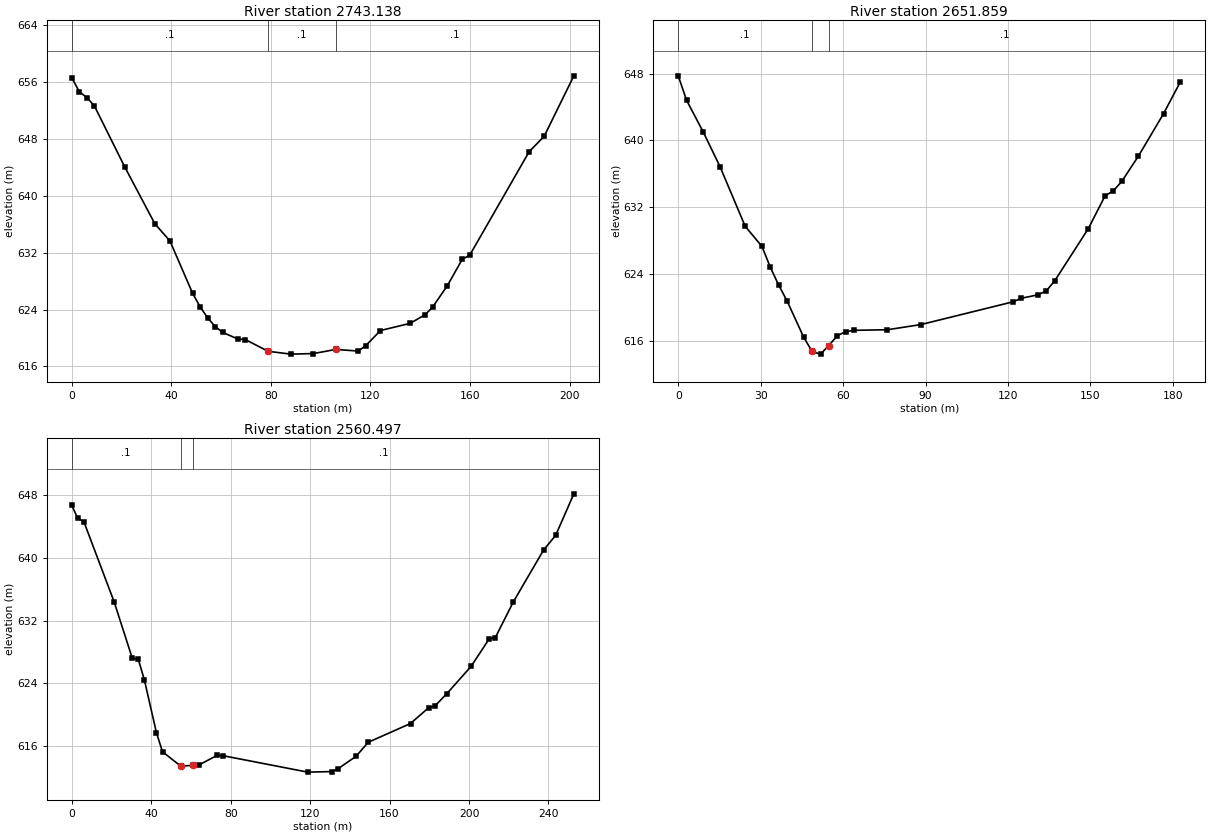
Type RM Length L Ch R = 1 ,2743.138,85.89,91.28,75.2
XS GIS Cut Line= 3
     625039.7174    4339854.6925     625073.3268    4339949.0125
     625101.8946    4340046.5158
#Sta/Elev= 30
       0  656.61    3.03  654.62    6.07  653.81     9.1  652.62   21.24  644.08
   33.38  636.06   39.44  633.65   48.55  626.28   51.58  624.37   54.62  622.82
   57.65   621.6   60.68  620.78   66.75  619.85   69.79  619.77   78.89  618.13
   87.99  617.73   97.09  617.81  106.11  618.39  115.07  618.16  118.06   618.9
  124.04  621.05  135.99  622.06  141.97  623.28  144.95  624.32  150.93  627.37
  156.91  631.07   159.9  631.64   183.8  646.21  189.78  648.34  201.73  656.86
#Mann= 3 , 0 , 0
       0      .1       0   78.89      .1       0  106.11      .1       0
Bank Sta=78.89,106.11
XS Rating Curve= 0 ,0
Exp/Cntr=0.3,0.1

Type RM Length L Ch R = 1 ,2651.859,89.69,91.36,102.35
XS GIS Cut Line= 2
     624959.5705    4339908.3259     625062.7582    4340059.1387
#Sta/Elev= 30
       0  647.73    3.05  644.79    9.14  640.98   15.23  636.84   24.36  629.72
   30.46  627.31    33.5  624.82   36.55  622.68   39.59  620.79   45.68  616.42
   48.73  614.73   51.78  614.41   54.82  615.44   57.87  616.61   60.91   617.1
   63.96  617.26   76.14  617.33   88.32  617.95  121.82  620.67  124.87   621.1
  130.96  621.51  134.01     622  137.05   623.2  149.23  629.42  155.33  633.35
  158.37  633.97  161.42  635.08  167.51  638.13  176.64   643.2  182.74     647
#Mann= 3 , 0 , 0
       0      .1       0   48.73      .1       0   54.82      .1       0
Bank Sta=48.73,54.82
XS Rating Curve= 0 ,0
Exp/Cntr=0.3,0.1

Type RM Length L Ch R = 1 ,2560.497,94.08,91.72,82.54
XS GIS Cut Line= 2
     624904.6694    4339936.1072     624937.0809    4340186.8004
#Sta/Elev= 30
       0  646.62    3.05  644.97    6.09  644.56   21.32  634.38   30.46  627.21
    33.5  627.06   36.55  624.46   42.64  617.73   45.68  615.32   54.82   613.5
   60.91  613.58   63.96  613.63   73.09  614.85   76.14  614.82  118.78  612.73
  130.96   612.8     134  613.15  143.14  614.74  149.23  616.52  170.55  618.91
  179.69  620.92  182.73  621.11  188.82   622.7  201.01  626.16  210.14  629.66
  213.19   629.8  222.32  634.37  237.55  640.96  243.64  642.83  252.78   648.1
#Mann= 3 , 0 , 0
       0      .1       0   54.82      .1       0   60.91      .1       0
Bank Sta=54.82,60.91
XS Rating Curve= 0 ,0
Exp/Cntr=0.3,0.1