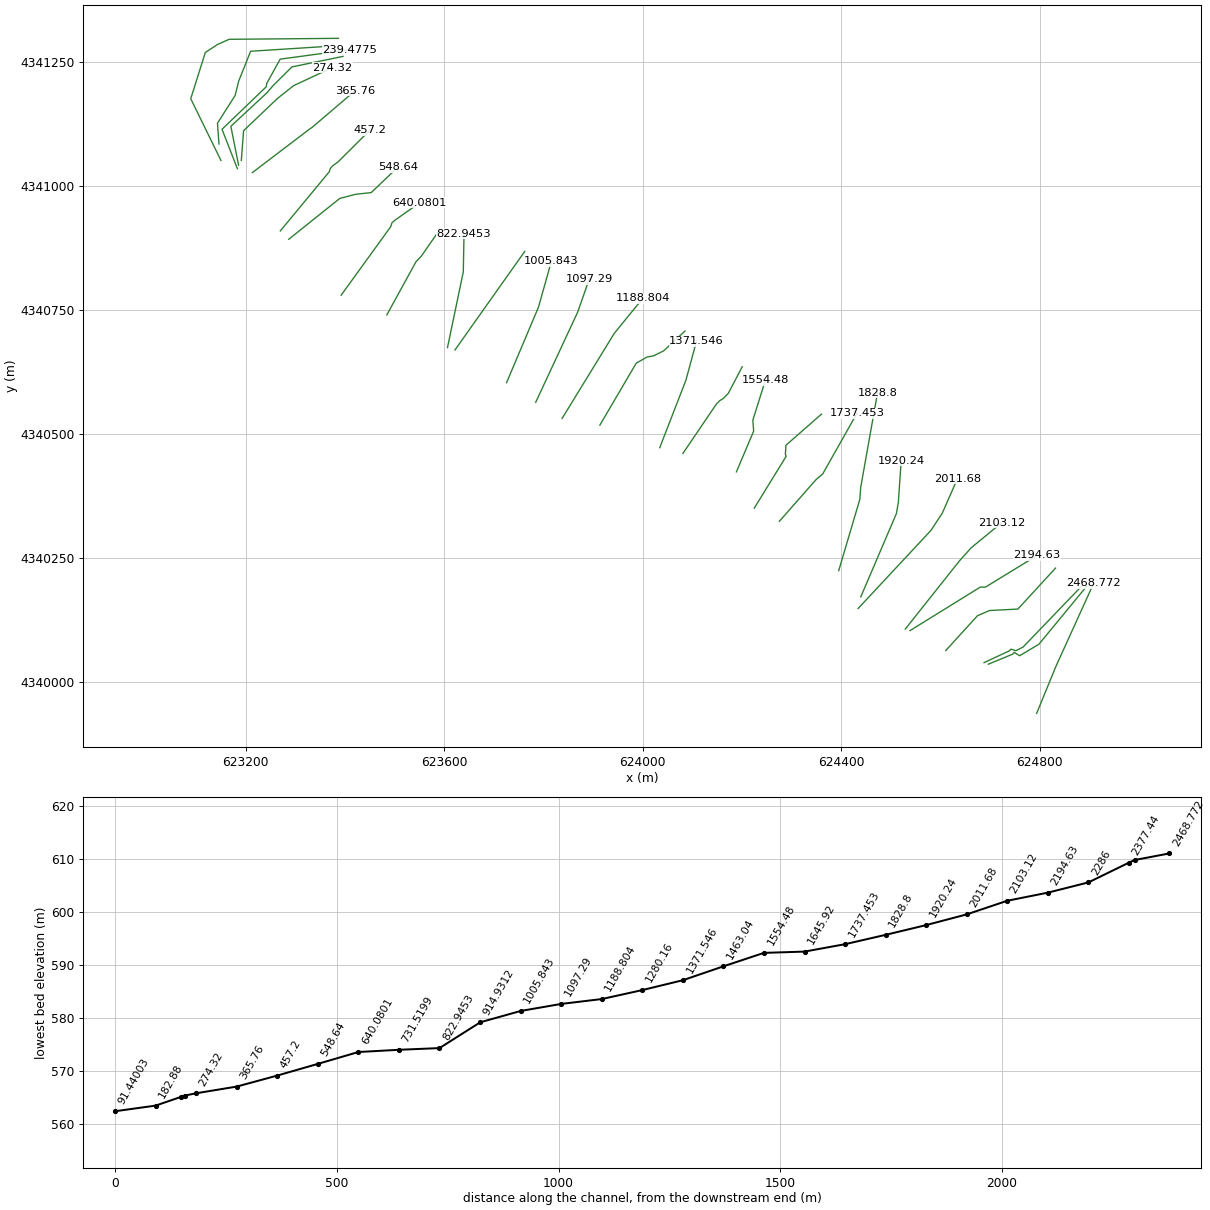
HEC-RAS study LeadmineRun.prj: LeadmineRun

--- LeadmineRun.g01 (geometry) --- (continued)

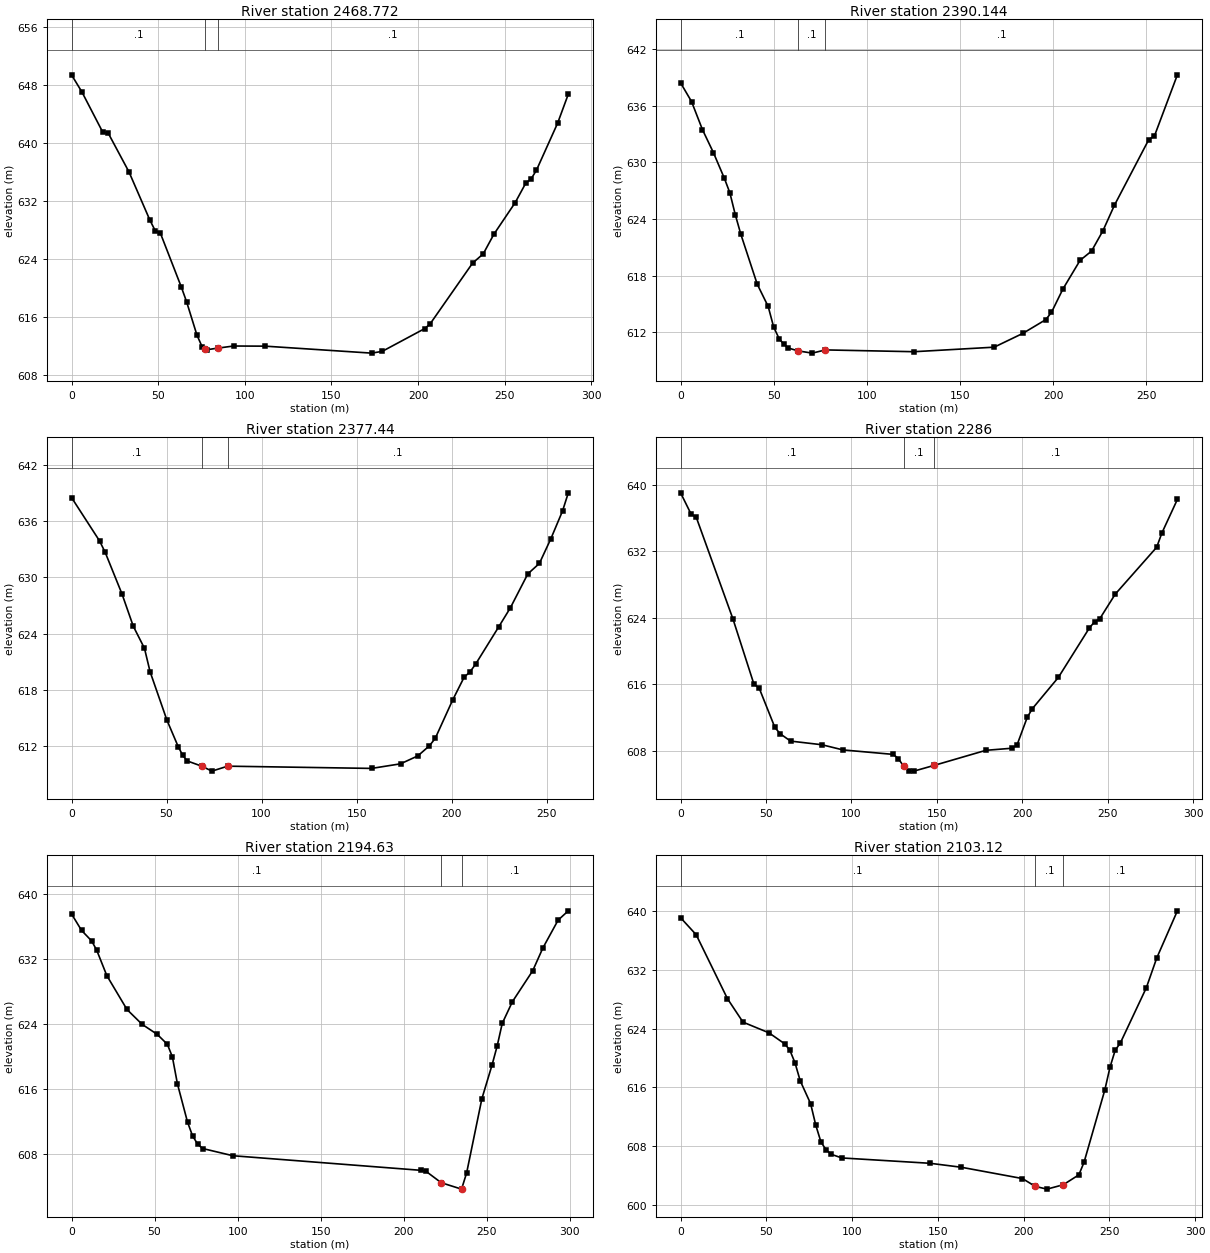
Type RM Length L Ch R = 1 ,2468.772,95.55,78.63,55.34
XS GIS Cut Line= 3
     624793.5441    4339937.4301     624832.4614    4340032.3508
     624908.6381    4340200.0296
#Sta/Elev= 30
       0  649.37    6.03     647    18.1  641.44   21.12  641.37   33.19  635.99
   45.26  629.35   48.28  627.92   51.29  627.57   63.36  620.16   66.38  618.15
   72.42  613.51   75.43   611.9   77.31  611.66   78.45  611.52   84.49  611.73
   93.54  612.02   111.8     612  173.19  611.04  179.33  611.28  203.88  614.42
  206.95  615.05  231.51  623.44  237.65  624.71  243.79  627.41  256.07  631.76
   262.2  634.45  265.27  635.03  268.34  636.22  280.62  642.73  286.76  646.71
#Mann= 3 , 0 , 0
       0      .1       0   77.31      .1       0   84.49      .1       0
Bank Sta=77.31,84.49
XS Rating Curve= 0 ,0
Exp/Cntr=0.3,0.1

Type RM Length L Ch R = 1 ,2390.144,9.4,12.7,17.84
XS GIS Cut Line= 6
     624696.0979    4340036.5168     624745.0243    4340056.6642
     624748.4131    4340060.3122     624759.2346    4340053.5222
     624798.2277    4340076.8828     624894.0066    4340193.1504
#Sta/Elev= 30
       0   638.4    5.88  636.42   11.76  633.44   17.64  631.01   23.52  628.29
   26.46  626.76    29.4  624.42   32.34  622.38   41.15  617.09   47.03  614.73
   49.97  612.56   52.91  611.32    55.4  610.73   57.89  610.33      63  610.03
   70.67  609.79    77.8  610.13  125.35  609.94  168.39  610.42  183.77  611.88
  196.06  613.33  199.14   614.1  205.28  616.57  214.51  619.61  220.66  620.59
   226.8  622.75  232.95  625.44   251.4  632.39  254.47  632.79  266.77  639.25
#Mann= 3 , 0 , 0
       0      .1       0      63      .1       0    77.8      .1       0
Bank Sta=63,77.8
XS Rating Curve= 0 ,0
Exp/Cntr=0.3,0.1

Type RM Length L Ch R = 1 ,2377.44 ,95.11,91.44,73.94
XS GIS Cut Line= 6
     624687.6312    4340039.6918     624738.4648    4340063.4441
     624741.7721    4340066.8837     624751.6219    4340063.6778
     624766.3543    4340071.1958     624886.5983    4340196.3254
#Sta/Elev= 30
       0  638.53   14.77  633.89   17.72  632.67   26.58  628.22   32.48  624.79
   38.39  622.42   41.34  619.92    50.2  614.75   56.11  611.93   58.49     611
   60.88  610.39   68.65  609.82   73.86   609.3   82.17  609.83  157.89  609.59
  173.11  610.08  182.24  610.93  188.33  612.01  191.38   612.8  200.51  616.88
   206.6  619.34  209.64  619.89  212.69  620.75  224.87  624.74  230.95  626.76
  240.09  630.37  246.18  631.49  252.27  634.15  258.36  637.09   261.4  639.03
#Mann= 3 , 0 , 0
       0      .1       0   68.65      .1       0   82.17      .1       0
Bank Sta=68.65,82.17
XS Rating Curve= 0 ,0
Exp/Cntr=0.3,0.1

Type RM Length L Ch R = 1 ,2286    ,55.63,91.37,80.88
XS GIS Cut Line= 5
     624610.3727    4340064.0335     624674.3453    4340134.2329
     624698.6945    4340144.6717     624755.7731    4340147.6369
     624831.5648    4340230.1922
#Sta/Elev= 30
       0  639.02    6.13  636.47    9.19  636.07   30.64  623.86   42.89  616.04
   45.96  615.56   55.15  610.83   58.21  610.07   64.34  609.18   82.72  608.74
   94.98  608.12  124.48  607.58  127.48  607.06  130.49  606.16   133.5  605.59
  136.51  605.57  148.54  606.27  178.62  608.07  193.77  608.32   196.8  608.68
  202.86  612.05  205.88  613.09  221.03  616.83   239.2  622.78  242.23  623.52
  245.26  623.88  254.35  626.85  278.58  632.48  281.61  634.19  290.69  638.23
#Mann= 3 , 0 , 0
       0      .1       0  130.49      .1       0  148.54      .1       0
Bank Sta=130.49,148.54
XS Rating Curve= 0 ,0
Exp/Cntr=0.3,0.1

Type RM Length L Ch R = 1 ,2194.63 ,72.26,91.51,90.43
XS GIS Cut Line= 4
     624538.4059    4340104.2502     624680.4307    4340192.1327
     624690.1033    4340191.6962     624794.5231    4340255.5922
#Sta/Elev= 30
       0  637.59    6.07  635.55   12.15  634.25   15.18  633.11   21.26  629.98
    33.4   625.8   42.51  623.97   51.62  622.73    57.7  621.51   60.73  619.96
   63.77  616.63   69.84  611.92   72.88  610.21   75.92   609.2   78.95  608.65
   97.17  607.76  210.36  605.96  213.42  605.84  222.61  604.43  234.85  603.64
  237.91  605.65  247.09   614.8  253.21  618.96  256.27  621.28  259.33  624.08
  265.45  626.76  277.69  630.58  283.81  633.39     293  636.83  299.12  637.97
#Mann= 3 , 0 , 0
       0      .1       0  222.61      .1       0  234.85      .1       0
Bank Sta=222.61,234.85
XS Rating Curve= 0 ,0
Exp/Cntr=0.3,0.1

Type RM Length L Ch R = 1 ,2103.12 ,84.78,91.44,96.13
XS GIS Cut Line= 4
     624528.8809    4340107.4252      624638.283    4340245.1293
     624661.8448    4340271.2843     624722.5563     4340321.209
#Sta/Elev= 30
       0   639.1     9.1  636.78   27.29  628.08   36.39  624.87   51.55  623.41
   60.65  621.92   63.68  621.06   66.71  619.33   69.74  616.88   75.81  613.76
   78.84  610.81   81.87  608.52    84.9  607.45   87.94  606.85      94  606.36
  145.55  605.63  163.74  605.09  199.34  603.55  206.81  602.48  213.65  602.11
  223.17  602.71  232.24  604.06  235.26  605.78  247.35  615.61  250.38  618.72
   253.4  621.03  256.42  622.03  271.54  629.54  277.59  633.58  289.68  640.04
#Mann= 3 , 0 , 0
       0      .1       0  206.81      .1       0  223.17      .1       0
Bank Sta=206.81,223.17
XS Rating Curve= 0 ,0
Exp/Cntr=0.3,0.1

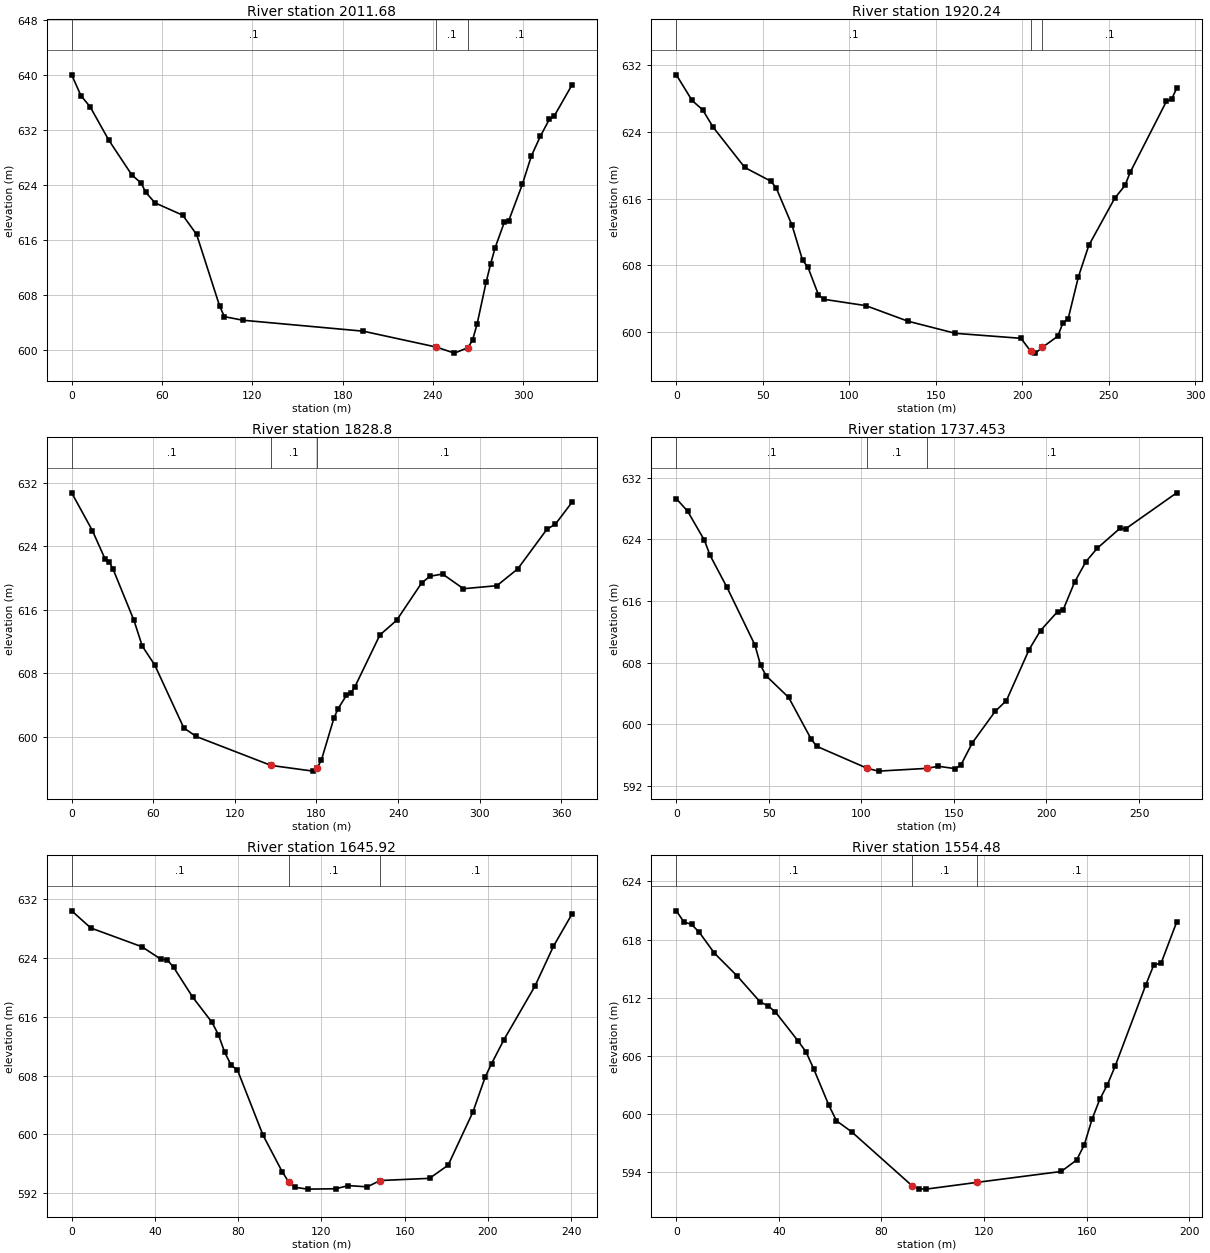
Type RM Length L Ch R = 1 ,2011.68 ,73.51,91.44,94.86
XS GIS Cut Line= 4
     624433.8071    4340148.7885     624580.5768     4340306.135
     624603.6475     4340341.382     624633.8325    4340410.1974
#Sta/Elev= 30
       0  639.98    6.15  636.95    12.3  635.32   24.59  630.51   39.96  625.43
   46.11  624.26   49.18  622.92   55.33  621.38   73.77  619.58      83  616.78
   98.36  606.33  101.44  604.84  113.73  604.32  193.66  602.73  242.25  600.42
  254.29  599.54  263.31  600.34  266.32  601.44  269.32  603.75  275.33  609.84
  278.34  612.53  281.34  614.87  287.36  618.53  290.36  618.79  299.38  624.06
  305.39  628.19   311.4  631.07  317.41  633.54  320.42  633.93  332.44  638.54
#Mann= 3 , 0 , 0
       0      .1       0  242.25      .1       0  263.31      .1       0
Bank Sta=242.25,263.31
XS Rating Curve= 0 ,0
Exp/Cntr=0.3,0.1

Type RM Length L Ch R = 1 ,1920.24 ,80.72,91.44,84.45
XS GIS Cut Line= 5
     624439.0988    4340172.0719     624510.8959    4340339.9753
     624515.1894    4340364.6632     624515.2134    4340368.6022
     624520.5906    4340446.1808
#Sta/Elev= 30
       0   630.8    9.13  627.73   15.22  626.62    21.3  624.54   39.57  619.72
   54.78  618.07   57.83  617.24   66.96  612.79   73.04  608.61   76.09  607.81
   82.17  604.51   85.22  603.96  109.57   603.2  133.91  601.34  161.31  599.89
  199.32  599.29  204.88  597.76  207.67  597.52  211.61   598.2  220.58  599.54
  223.57  601.13  226.56   601.6  232.54  606.66  238.53   610.4  253.48  616.03
  259.46  617.57  262.45  619.14  283.39  627.62  286.38  627.87  289.37   629.2
#Mann= 3 , 0 , 0
       0      .1       0  204.88      .1       0  211.61      .1       0
Bank Sta=204.88,211.61
XS Rating Curve= 0 ,0
Exp/Cntr=0.3,0.1

Type RM Length L Ch R = 1 ,1828.8  ,100.94,91.35,84.55
XS GIS Cut Line= 4
     624394.6487    4340224.9887     624437.1603    4340368.4459
     624439.0467    4340393.1825     624472.9655    4340583.7644
#Sta/Elev= 30
       0  630.71   15.27  625.94   24.43  622.43   27.48  622.06   30.54  621.06
    45.8  614.65   51.91  611.42   61.07  609.04   82.45  601.12   91.61  600.04
  146.57   596.4   177.5  595.68  180.58   596.1  183.65  597.07  192.87  602.36
  195.94  603.55  202.09  605.22  205.16  605.49  208.23  606.28  226.67  612.82
  238.96  614.66  257.39  619.37  263.54  620.21  272.76  620.49  288.12  618.64
   312.7  619.02  328.06  621.14  349.57  626.14  355.72  626.76  368.01  629.54
#Mann= 3 , 0 , 0
       0      .1       0  146.57      .1       0  180.58      .1       0
Bank Sta=146.57,180.58
XS Rating Curve= 0 ,0
Exp/Cntr=0.3,0.1

Type RM Length L Ch R = 1 ,1737.453,81.79,91.53,94.04
XS GIS Cut Line= 4
     624275.0568    4340324.4722     624349.2798    4340408.7486
     624362.2832    4340419.6915     624431.6904    4340542.4893
#Sta/Elev= 30
       0  629.27    6.07  627.66   15.18  623.88   18.21  621.93   27.32  617.79
   42.49  610.28   45.53  607.65   48.56  606.28    60.7  603.48   72.84  598.08
   75.88  597.14   103.2  594.28  109.27  593.92  135.43  594.28  141.56  594.55
  150.76  594.24  153.83  594.75  159.96   597.6  172.23  601.66  178.36  603.08
  190.62   609.7  196.76  612.16  205.96  614.61  209.02  614.86  215.16  618.43
  221.29   621.1  227.42  622.84  239.69  625.42  242.75  625.36  270.35  630.03
#Mann= 3 , 0 , 0
       0      .1       0   103.2      .1       0  135.43      .1       0
Bank Sta=103.2,135.43
XS Rating Curve= 0 ,0
Exp/Cntr=0.3,0.1

Type RM Length L Ch R = 1 ,1645.92 ,96.21,91.44,89
XS GIS Cut Line= 5
     624224.5389    4340351.0717     624288.7959    4340455.4741
     624287.1918    4340459.4599     624288.2985    4340477.6972
     624360.0058    4340540.5137
#Sta/Elev= 30
       0  630.44    9.19   628.1   33.71  625.55   42.91  623.84   45.97  623.75
   49.04  622.72   58.23  618.65   67.43  615.25   70.49  613.57   73.56  611.15
   76.62  609.41   79.68  608.74   91.94  599.88  101.14  594.91   104.2  593.54
  107.27  592.77   113.4  592.52  126.89  592.57  132.98     593  142.11  592.83
  148.14  593.69  171.97  593.99  180.91  595.78  192.82  603.02  198.78  607.83
  201.76   609.6  207.72  612.87  222.62  620.17  231.55  625.62  240.49  630.02
#Mann= 3 , 0 , 0
       0      .1       0   104.2      .1       0  148.14      .1       0
Bank Sta=104.2,148.14
XS Rating Curve= 0 ,0
Exp/Cntr=0.3,0.1

Type RM Length L Ch R = 1 ,1554.48 ,94.01,91.44,72.81
XS GIS Cut Line= 4
     624188.5555    4340424.0968     624223.2799    4340506.2861
      624221.571    4340528.0736     624246.7639    4340608.2472
#Sta/Elev= 30
       0  620.96    2.97  619.81    5.95  619.56    8.92  618.76   14.87  616.59
   23.79  614.23   32.72  611.56   35.69  611.19   38.66  610.53   47.59  607.51
   50.56  606.43   53.53   604.7   59.48  600.92   62.46  599.32    68.4  598.18
   91.96  592.62   94.69  592.31   97.42  592.28  117.08  592.97   150.1   594.1
   156.1  595.28   159.1  596.86   162.1  599.48   165.1  601.52   168.1  603.05
  171.11  604.95  183.11  613.36  186.11  615.34  189.11  615.62  195.12  619.81
#Mann= 3 , 0 , 0
       0      .1       0   91.96      .1       0  117.08      .1       0
Bank Sta=91.96,117.08
XS Rating Curve= 0 ,0
Exp/Cntr=0.3,0.1

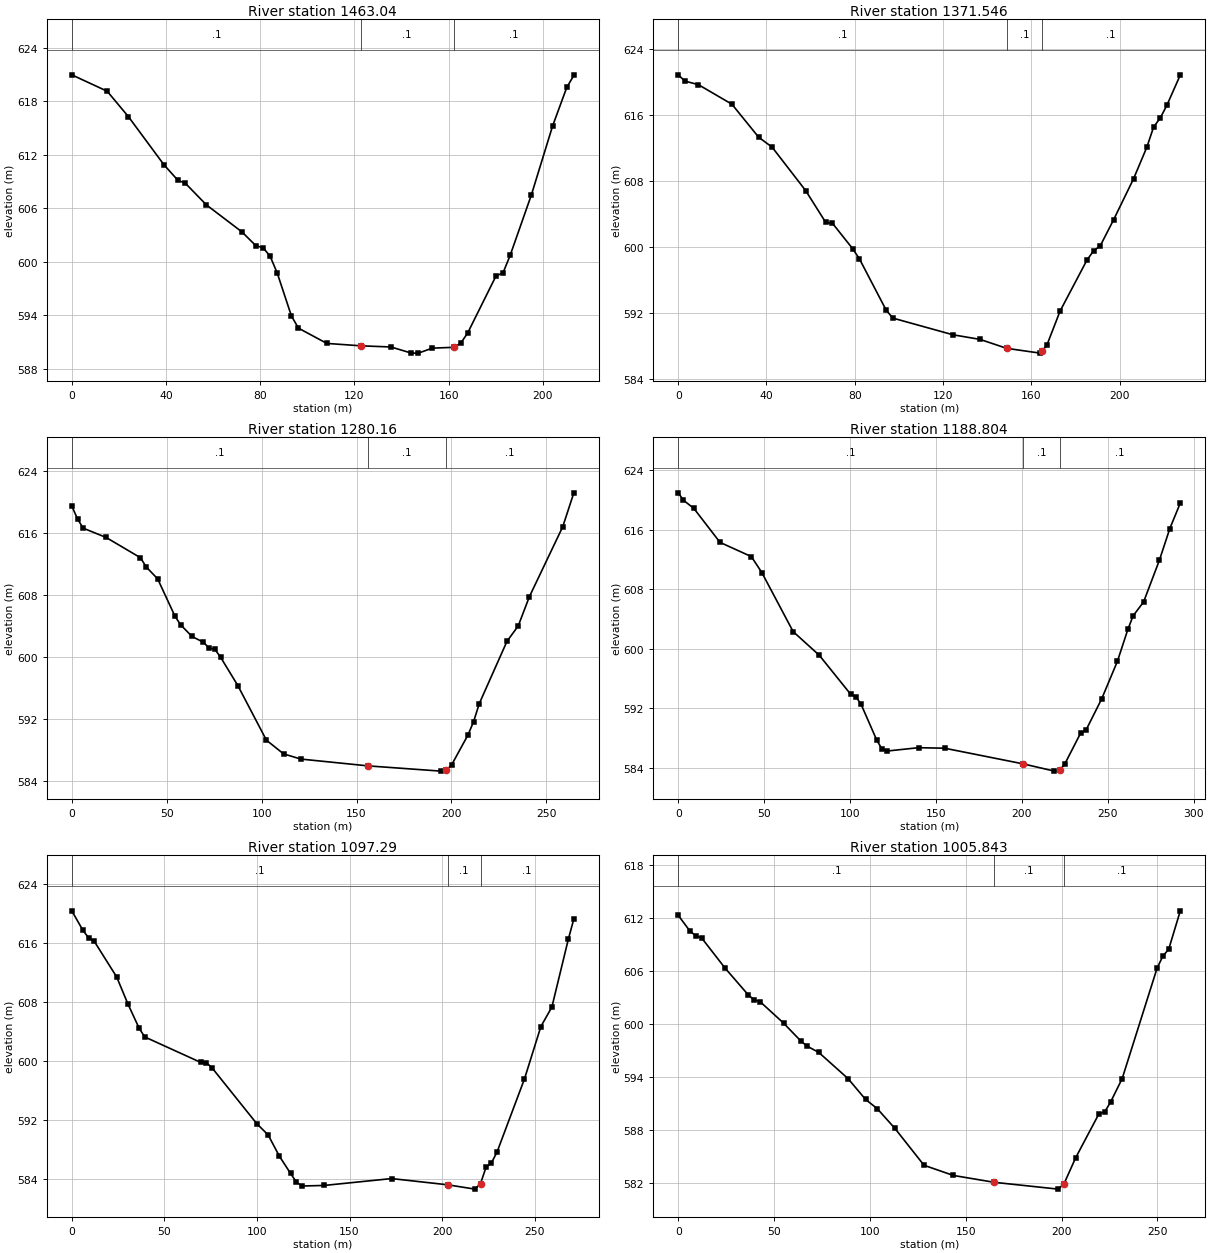
Type RM Length L Ch R = 1 ,1463.04 ,78.1,91.49,94.28
XS GIS Cut Line= 6
     624080.6053    4340461.1386     624148.1832    4340560.7006
     624154.8665    4340567.5618     624162.0779    4340571.9329
     624172.3188    4340582.5068     624200.1972    4340635.7639
#Sta/Elev= 30
       0  620.96   15.04  619.12   24.07  616.26   39.11  610.88   45.12  609.11
   48.13  608.82   57.16  606.37    72.2  603.35   78.21  601.78   81.22  601.57
   84.23   600.6   87.24  598.72   93.26  593.91   96.26  592.54   108.3  590.83
  122.72  590.56  135.53  590.43  144.23  589.74  147.17  589.74  153.06   590.3
  162.08  590.39  165.08  590.83  168.09     592  180.11  598.39  183.12  598.76
  186.12   600.7  195.14  607.49  204.16  615.23  210.17  619.55  213.17   620.9
#Mann= 3 , 0 , 0
       0      .1       0  122.72      .1       0  162.08      .1       0
Bank Sta=122.72,162.08
XS Rating Curve= 0 ,0
Exp/Cntr=0.3,0.1

Type RM Length L Ch R = 1 ,1371.546,110.63,91.39,79.84
XS GIS Cut Line= 3
     624034.0385    4340472.7803     624086.7628    4340608.7664
      624108.122    4340687.6224
#Sta/Elev= 30
       0  620.87    3.04  620.11    9.12  619.68   24.31  617.31   36.46   613.3
   42.54   612.1   57.73  606.84   66.85  602.97   69.89  602.87      79   599.8
   82.04  598.59   94.19  592.36   97.23  591.37  124.58  589.34  136.73  588.79
  148.88   587.7     164  587.12  164.81  587.37  167.03  588.06  173.08  592.23
  185.19  598.38  188.21  599.52  191.24  600.12  197.29  603.28  206.37  608.27
  212.42  612.12  215.44  614.54  218.47  615.64   221.5   617.2  227.55  620.86
#Mann= 3 , 0 , 0
       0      .1       0  148.88      .1       0  164.81      .1       0
Bank Sta=148.88,164.81
XS Rating Curve= 0 ,0
Exp/Cntr=0.3,0.1

Type RM Length L Ch R = 1 ,1280.16 ,74.43,91.36,95.79
XS GIS Cut Line= 6
     623913.3883    4340518.2887     623986.6747    4340643.1227
      624008.688    4340655.6111     624021.3256    4340657.7558
     624041.7875    4340667.8877     624084.8386    4340707.7307
#Sta/Elev= 30
       0  619.55    3.02  617.86    6.03  616.67   18.09  615.47   36.19  612.85
    39.2  611.66   45.24  610.12   54.28  605.33    57.3  604.19   63.33  602.67
   69.36  601.92   72.38  601.16   75.39  601.01   78.41  599.98   87.46  596.33
  102.54  589.26  111.58  587.49  120.63  586.82     156  585.94  194.42  585.26
  197.27  585.36  200.13  586.08  208.77  589.96   211.7  591.67  214.63  593.97
   229.3  602.06  235.17  604.02  241.03  607.79  258.63  616.85  264.49  621.24
#Mann= 3 , 0 , 0
       0      .1       0     156      .1       0  197.27      .1       0
Bank Sta=156,197.27
XS Rating Curve= 0 ,0
Exp/Cntr=0.3,0.1

Type RM Length L Ch R = 1 ,1188.804,83.27,91.51,92.73
XS GIS Cut Line= 3
      623837.294    4340531.7825     623942.1716    4340702.8778
      624000.013    4340773.8767
#Sta/Elev= 30
       0  620.97    3.04  619.97    9.12  618.87   24.32  614.31   42.57   612.4
   48.65  610.26   66.89  602.32    82.1  599.14  100.34  593.91  103.38  593.58
  106.42  592.56  115.54  587.74  118.58  586.55  121.62  586.27  139.87  586.72
  155.07  586.65  200.68  584.55     219  583.57  222.05  583.68   225.1  584.57
  234.26  588.69  237.31  589.06  246.47  593.27  255.63  598.32  261.73  602.62
  264.79  604.44  270.89  606.31  280.05  611.89  286.15  616.17  292.26   619.6
#Mann= 3 , 0 , 0
       0      .1       0  200.68      .1       0  222.05      .1       0
Bank Sta=200.68,222.05
XS Rating Curve= 0 ,0
Exp/Cntr=0.3,0.1

Type RM Length L Ch R = 1 ,1097.29 ,81.83,91.45,84.83
XS GIS Cut Line= 3
     623784.1126    4340564.3263     623868.5085    4340745.6123
     623892.0628    4340812.7705
#Sta/Elev= 30
       0  620.37    6.06  617.71    9.09  616.71   12.12  616.25   24.24  611.41
    30.3  607.76   36.36  604.47   39.39  603.28   69.69  599.82   72.72  599.78
   75.75  599.09   99.98   591.5  106.04     590   112.1  587.12  118.16  584.78
  121.19  583.64  124.22  583.07  136.34  583.15   172.7  584.08  202.93  583.24
  217.76  582.65  220.73   583.4  223.69  585.59  226.66  586.23  229.62  587.65
  244.45  597.57  253.34  604.69  259.28  607.33  268.17  616.53  271.14  619.27
#Mann= 3 , 0 , 0
       0      .1       0  202.93      .1       0  220.73      .1       0
Bank Sta=202.93,220.73
XS Rating Curve= 0 ,0
Exp/Cntr=0.3,0.1

Type RM Length L Ch R = 1 ,1005.843,93.56,90.91,85.48
XS GIS Cut Line= 3
      623725.375    4340603.8551     623789.5739    4340755.6988
     623815.8627    4340849.1244
#Sta/Elev= 30
       0  612.31    6.11  610.53    9.16  609.99   12.21  609.75   24.42  606.34
   36.63  603.28   39.69  602.73   42.74  602.53   54.95  600.11   64.11  598.05
   67.16  597.51   73.27   596.8   88.53  593.84   97.69  591.48   103.8  590.43
  112.96  588.21  128.22  584.02  143.49  582.87  164.86  582.09  198.22  581.32
  201.25  581.93  207.32  584.87  219.45  589.84  222.48  590.07  225.52  591.17
  231.58  593.83  249.78  606.32  252.81   607.7  255.85  608.47  261.91  612.82
#Mann= 3 , 0 , 0
       0      .1       0  164.86      .1       0  201.25      .1       0
Bank Sta=164.86,201.25
XS Rating Curve= 0 ,0
Exp/Cntr=0.3,0.1

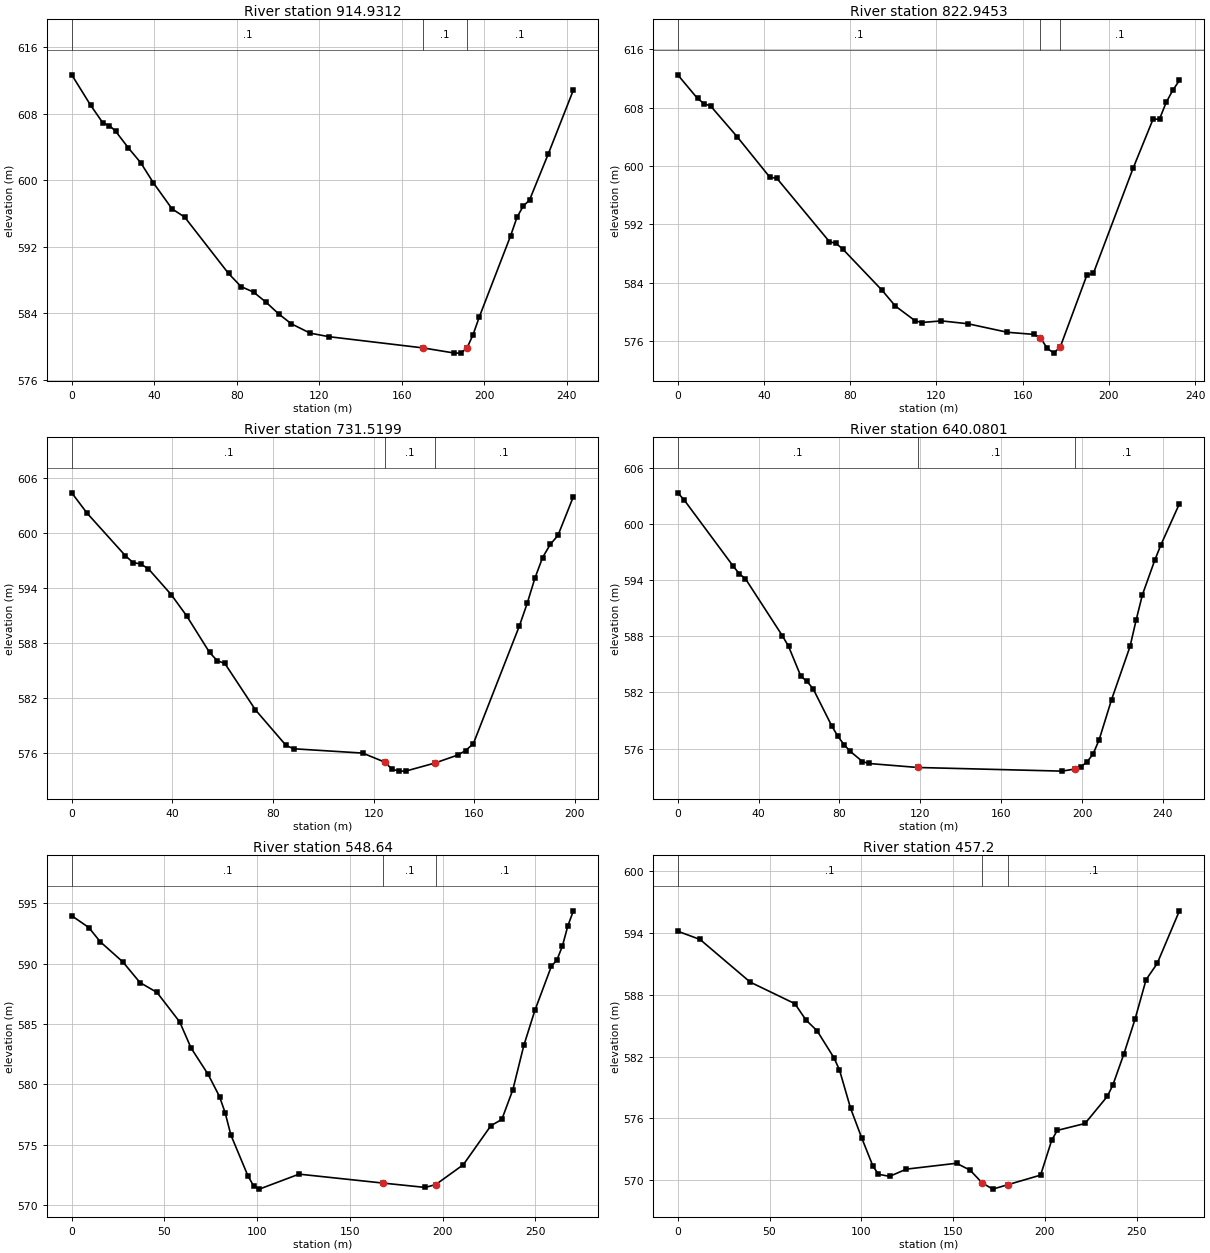
Type RM Length L Ch R = 1 ,914.9312,83.32,91.99,98.06
XS GIS Cut Line= 2
     623621.3935    4340669.7365     623761.8876    4340868.1744
#Sta/Elev= 30
       0  612.69    9.12  609.04    15.2  606.86   18.24  606.59   21.27   605.9
   27.35  603.92   33.43  602.11   39.51  599.71   48.63  596.55   54.71  595.57
   75.98  588.78   82.06   587.2   88.14  586.53   94.22  585.31  100.29  583.91
  106.37  582.73  115.49   581.6  124.61  581.17   170.2  579.82  185.39   579.2
  188.43  579.19  191.47  579.75  194.51  581.41  197.55  583.56  212.75  593.34
  215.79  595.54  218.82  596.89  221.86  597.61  230.98  603.18  243.14  610.87
#Mann= 3 , 0 , 0
       0      .1       0   170.2      .1       0  191.47      .1       0
Bank Sta=170.2,191.47
XS Rating Curve= 0 ,0
Exp/Cntr=0.3,0.1

Type RM Length L Ch R = 1 ,822.9453,100.11,91.43,85.96
XS GIS Cut Line= 3
     623606.3122     4340674.499     623638.1717    4340827.1765
     623639.6498    4340903.8932
#Sta/Elev= 30
       0  612.49    9.17  609.25   12.23  608.53   15.29   608.2   27.52  604.01
   42.81  598.41   45.87  598.33   70.34  589.61    73.4  589.37   76.45  588.62
    94.8  582.93  100.92  580.78  110.09  578.76  113.15  578.52  122.33  578.74
  134.56  578.35  152.91  577.18  165.17  576.89  168.24  576.42  171.31  575.01
  174.38  574.32  177.45  575.18  189.73  584.98   192.8  585.27  211.21  599.67
  220.42  606.37  223.49  606.44  226.56   608.7  229.63  610.38   232.7  611.72
#Mann= 3 , 0 , 0
       0      .1       0  168.24      .1       0  177.45      .1       0
Bank Sta=168.24,177.45
XS Rating Curve= 0 ,0
Exp/Cntr=0.3,0.1

Type RM Length L Ch R = 1 ,731.5199,87.15,91.44,89.48
XS GIS Cut Line= 4
     623484.0745    4340740.3804     623542.6259     4340847.141
     623553.8704    4340859.1886     623588.8497    4340909.4495
#Sta/Elev= 30
       0  604.38    6.09  602.16   21.31  597.52   24.35  596.77    27.4  596.61
   30.44   596.1   39.57  593.26   45.66  590.96   54.79  586.96   57.84  586.06
   60.88  585.75   73.06  580.68   85.23   576.8   88.28  576.44  115.67  575.97
  124.51  574.98  127.26  574.23     130     574  132.75     574  144.37  574.88
  153.55  575.76  156.61  576.25  159.67  576.98  178.04  589.88  181.11  592.32
  184.17  595.06  187.23  597.32  190.29  598.75  193.35  599.74  199.48  603.97
#Mann= 3 , 0 , 0
       0      .1       0  124.51      .1       0  144.37      .1       0
Bank Sta=124.51,144.37
XS Rating Curve= 0 ,0
Exp/Cntr=0.3,0.1

Type RM Length L Ch R = 1 ,640.0801,111.65,91.44,94.27
XS GIS Cut Line= 5
     623391.9993     4340780.068     623491.9646    4340918.2216
     623494.4369    4340926.0308     623500.8103    4340931.4936
     623550.7496    4340966.5996
#Sta/Elev= 30
       0  603.36    3.05  602.63   27.41  595.52   30.45   594.7    33.5  594.16
   51.77  588.06   54.81  586.93    60.9  583.73   63.95  583.18   66.99  582.38
   76.13  578.44   79.17  577.32   82.22  576.42   85.26  575.71   91.35  574.61
    94.4   574.4  118.76  573.97  190.16  573.58  196.27   573.8  199.32  574.04
  202.37  574.54  205.43   575.4  208.48  576.95  214.58  581.22  223.74  586.92
  226.79  589.78  229.84  592.44  235.95  596.14     239  597.79  248.16  602.19
#Mann= 3 , 0 , 0
       0      .1       0  118.76      .1       0  196.27      .1       0
Bank Sta=118.76,196.27
XS Rating Curve= 0 ,0
Exp/Cntr=0.3,0.1

Type RM Length L Ch R = 1 ,548.64  ,63.68,91.44,91.34
XS GIS Cut Line= 5
     623286.4304    4340892.7807     623389.2891    4340975.1242
      623421.497    4340983.4686     623452.5808    4340986.8473
     623506.2995    4341038.0372
#Sta/Elev= 30
       0  593.95    9.19  592.98   15.32  591.81   27.58  590.13   36.77  588.43
   45.96  587.61   58.22  585.17   64.35  583.01   73.54  580.83   79.67     579
   82.73  577.65    85.8  575.82   94.99  572.44   98.05  571.61  101.12  571.34
  122.57  572.58  167.87  571.84  190.61  571.48   196.3  571.72  211.14  573.36
  225.98  576.58  231.91  577.11  237.85  579.56  243.79  583.24  249.72  586.12
  258.63  589.78   261.6  590.29  264.56  591.44  267.53  593.13   270.5  594.36
#Mann= 3 , 0 , 0
       0      .1       0  167.87      .1       0   196.3      .1       0
Bank Sta=167.87,196.3
XS Rating Curve= 0 ,0
Exp/Cntr=0.3,0.1

Type RM Length L Ch R = 1 ,457.2   ,107.54,91.44,95.26
XS GIS Cut Line= 6
     623269.4441    4340909.6611     623368.2363    4341028.9929
     623370.1053    4341035.2421     623374.3238    4341040.3778
     623385.9074    4341048.7965      623450.198    4341112.8424
#Sta/Elev= 30
       0  594.17   12.15  593.37   39.49  589.23   63.79  587.14   69.87  585.55
   75.94   584.5   85.05   581.9   88.09  580.72   94.17  576.98  100.24   574.1
  106.32  571.38  109.35  570.58  115.43  570.38  124.54  571.08  151.88  571.65
  159.27  570.98  165.87  569.74  171.62  569.14  179.82  569.57  197.67   570.5
  203.72  573.88  206.75  574.84  221.87  575.51  233.97  578.13     237  579.22
  243.05  582.26   249.1  585.62  255.15  589.47   261.2  591.04   273.3  596.15
#Mann= 3 , 0 , 0
       0      .1       0  165.87      .1       0  179.82      .1       0
Bank Sta=165.87,179.82
XS Rating Curve= 0 ,0
Exp/Cntr=0.3,0.1

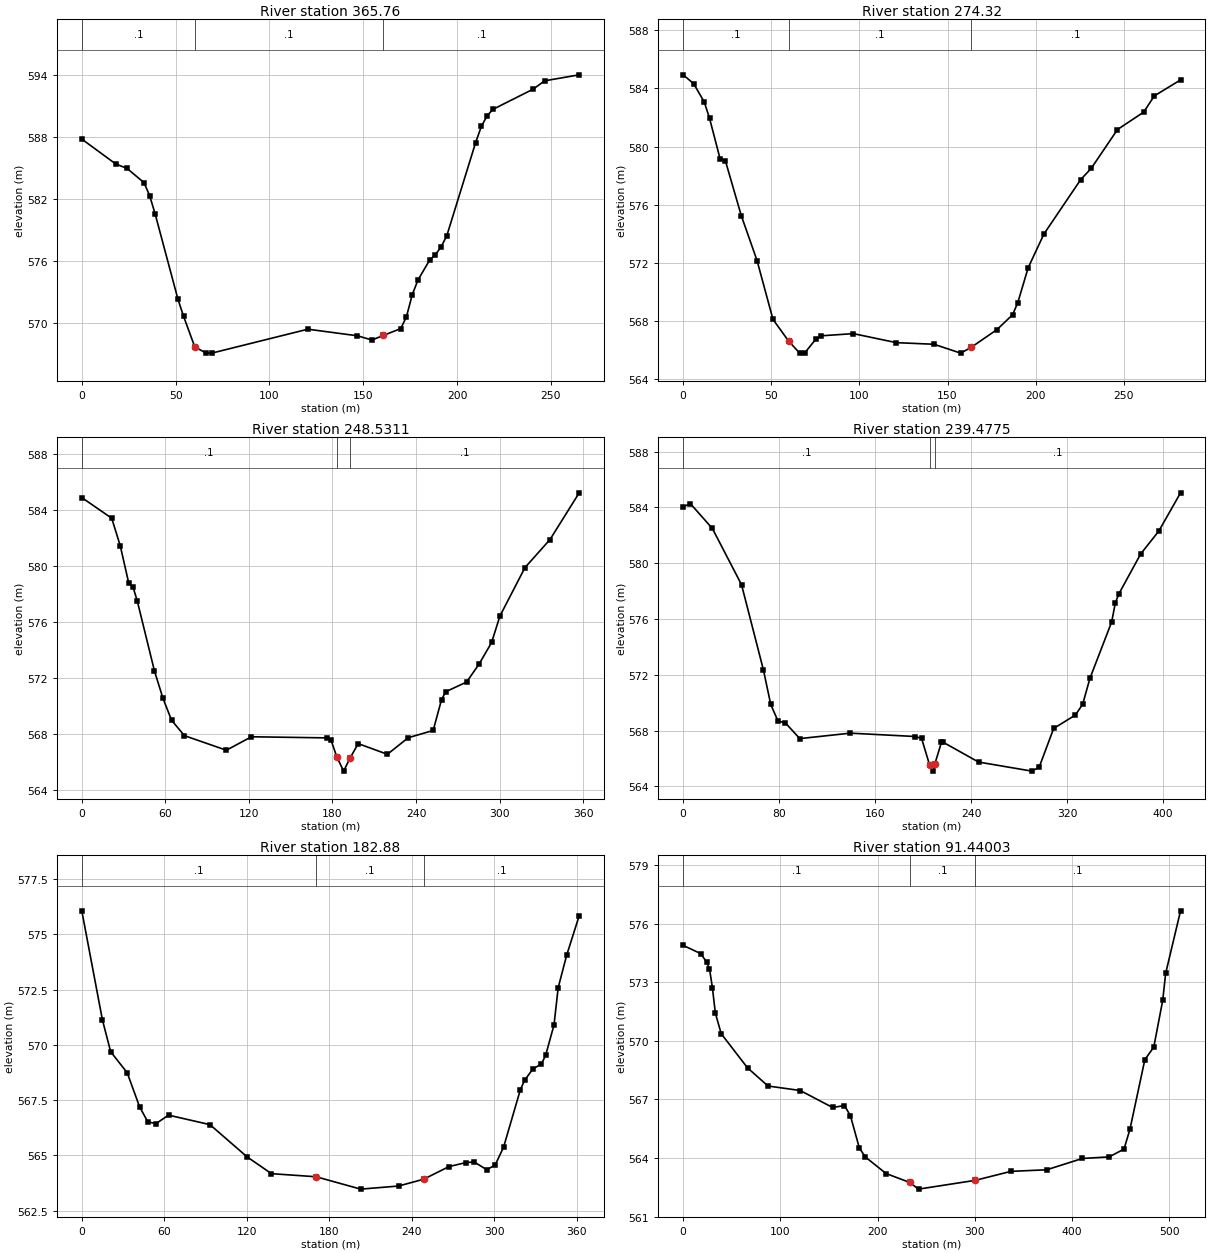
Type RM Length L Ch R = 1 ,365.76  ,93.59,91.44,91.03
XS GIS Cut Line= 4
     623213.0877    4341027.1364     623328.1283    4341114.6715
     623333.9028    4341118.6059     623420.2569    4341192.2367
#Sta/Elev= 30
       0  587.81   18.07   585.4   24.09  584.97   33.13  583.59   36.14  582.34
   39.15  580.51    51.2  572.31   54.21  570.64   60.23  567.65   66.26  567.07
   69.27  567.06  120.46  569.38  146.89  568.74  154.61  568.33  160.75  568.78
  169.95  569.44  173.01   570.6  176.08  572.73  179.15  574.16  185.28  576.06
  188.35  576.59  191.42  577.35  194.48  578.44  209.82  587.46  212.89  589.04
  215.95  590.06  219.02  590.69  240.49  592.65  246.63  593.46  265.03  594.04
#Mann= 3 , 0 , 0
       0      .1       0   60.23      .1       0  160.75      .1       0
Bank Sta=60.23,160.75
XS Rating Curve= 0 ,0
Exp/Cntr=0.3,0.1

Type RM Length L Ch R = 1 ,274.32  ,22.97,25.79,25.77
XS GIS Cut Line= 5
     623190.8627    4341051.7427     623195.4064    4341111.5223
     623263.8654     4341176.726     623296.2229     4341202.311
     623374.5128    4341238.9348
#Sta/Elev= 30
       0  584.93       6  584.32   11.99  583.06   14.99  581.94   20.98  579.15
   23.98  579.02   32.97  575.26   41.97  572.15   50.96  568.12   59.95  566.61
   66.05  565.81    69.1  565.83    75.2  566.75   78.25  566.99   96.55  567.14
  120.95  566.52  142.29  566.41  157.44   565.8  163.33  566.19  178.07  567.42
  186.91  568.44  189.85  569.27  195.74  571.67  204.69  573.99  225.55  577.73
  231.51   578.5  246.41  581.17  261.31  582.37  267.27  583.48  282.18  584.58
#Mann= 3 , 0 , 0
       0      .1       0   59.95      .1       0  163.33      .1       0
Bank Sta=59.95,163.33
XS Rating Curve= 0 ,0
Exp/Cntr=0.3,0.1

Type RM Length L Ch R = 1 ,248.5311,10.3,9.05,11.91
XS GIS Cut Line= 6
     623185.3064    4341042.2177     623169.7659    4341120.5004
     623242.3478    4341187.8263     623254.7303    4341202.2726
     623292.9678    4341240.1457     623395.6506    4341261.2931
#Sta/Elev= 30
       0  584.86   21.49  583.39   27.63  581.42   33.77  578.74   36.84  578.47
   39.91  577.46   52.18   572.5   58.32  570.54   64.46  568.99   73.67  567.89
  103.81  566.85  121.81  567.81  175.81  567.73  178.81  567.61  183.02   566.4
  187.99  565.36   192.6  566.29  198.49  567.32  219.42  566.56  234.36  567.74
   252.3  568.26   258.3  570.46  261.29  571.02  276.27  571.71  285.25  572.99
  294.24  574.53  300.23  576.42   318.2  579.87  336.17  581.87  357.14   585.2
#Mann= 3 , 0 , 0
       0      .1       0  183.02      .1       0   192.6      .1       0
Bank Sta=183.02,192.6
XS Rating Curve= 0 ,0
Exp/Cntr=0.3,0.1

Type RM Length L Ch R = 1 ,239.4775,49.67,56.6,54.71
XS GIS Cut Line= 6
     623182.9252    4341035.0739     623151.9688    4341114.4491
     623241.0425    4341200.0148     623242.2067    4341207.1057
     623269.1942    4341255.7891     623409.9381    4341274.7869
#Sta/Elev= 30
       0  584.04    6.09  584.26   24.34  582.49   48.68  578.46   66.94  572.35
   73.03  569.88   79.11  568.68    85.2  568.56   97.24  567.43  139.37  567.82
  193.55  567.58  198.81  567.44  205.57  565.51  208.07  565.12  209.78   565.6
  215.34  567.16  216.97  567.16  246.27  565.75  290.77   565.1  296.81  565.38
   308.9  568.16  327.03  569.12  333.07  569.89  339.12  571.75  357.25  575.79
  360.27  577.15  363.29  577.81  381.42  580.66  396.53   582.3  414.66  585.04
#Mann= 3 , 0 , 0
       0      .1       0  205.57      .1       0  209.78      .1       0
Bank Sta=205.57,209.78
XS Rating Curve= 0 ,0
Exp/Cntr=0.3,0.1

Type RM Length L Ch R = 1 ,182.88  ,112.9,91.44,83.84
XS GIS Cut Line= 6
     623145.8393    4341084.7164     623142.8251     4341126.642
     623178.3886    4341182.5433     623185.5258    4341211.3855
     623209.6312    4341271.6464     623368.2625    4341281.7702
#Sta/Elev= 30
       0  576.07   15.01  571.13   21.02  569.69   33.03  568.74   42.03   567.2
   48.06  566.51   54.08  566.44   63.11  566.82   93.23  566.39  120.26  564.93
     138  564.17  170.45  564.03   202.9  563.47  230.42  563.61  248.76  563.92
   267.1  564.49  279.32  564.67  285.44   564.7  294.61  564.35  300.72  564.56
  306.84  565.37  319.06  567.97  322.12   568.4  328.23  568.91  334.35  569.14
   337.4  569.52  343.52   570.9  346.57  572.59  352.69  574.05  361.86  575.85
#Mann= 3 , 0 , 0
       0      .1       0  170.45      .1       0  248.76      .1       0
Bank Sta=170.45,248.76
XS Rating Curve= 0 ,0
Exp/Cntr=0.3,0.1

Type RM Length L Ch R = 1 ,91.44003,64.06,91.44,55.68
XS GIS Cut Line= 6
     623149.8081    4341051.6435     623088.9538    4341175.9979
     623118.3109    4341269.1343      623143.146    4341285.4519
     623166.3721    4341295.7631     623386.6106    4341297.7065
#Sta/Elev= 30
       0  574.89   18.06  574.47   24.08  574.04   27.09   573.7    30.1  572.73
   33.11  571.43   39.13  570.37   66.21  568.62   87.28  567.69  120.39  567.46
   153.7  566.59  165.91  566.69  172.01  566.17  181.17  564.52  187.27  564.06
  208.63  563.21  233.05  562.75  242.04  562.41   300.4  562.86  337.11  563.32
  373.82   563.4  410.53  563.98  438.06  564.06  453.35  564.46  459.47  565.48
  474.77  569.04  483.94  569.68  493.12  572.07  496.18  573.46  511.48  576.66
#Mann= 3 , 0 , 0
       0      .1       0  233.05      .1       0   300.4      .1       0
Bank Sta=233.05,300.4
XS Rating Curve= 0 ,0
Exp/Cntr=0.3,0.1
LCMann Table=0

Chan Stop Cuts=-1
Use User Specified Reach Order=0
Composite Channel Slope=5